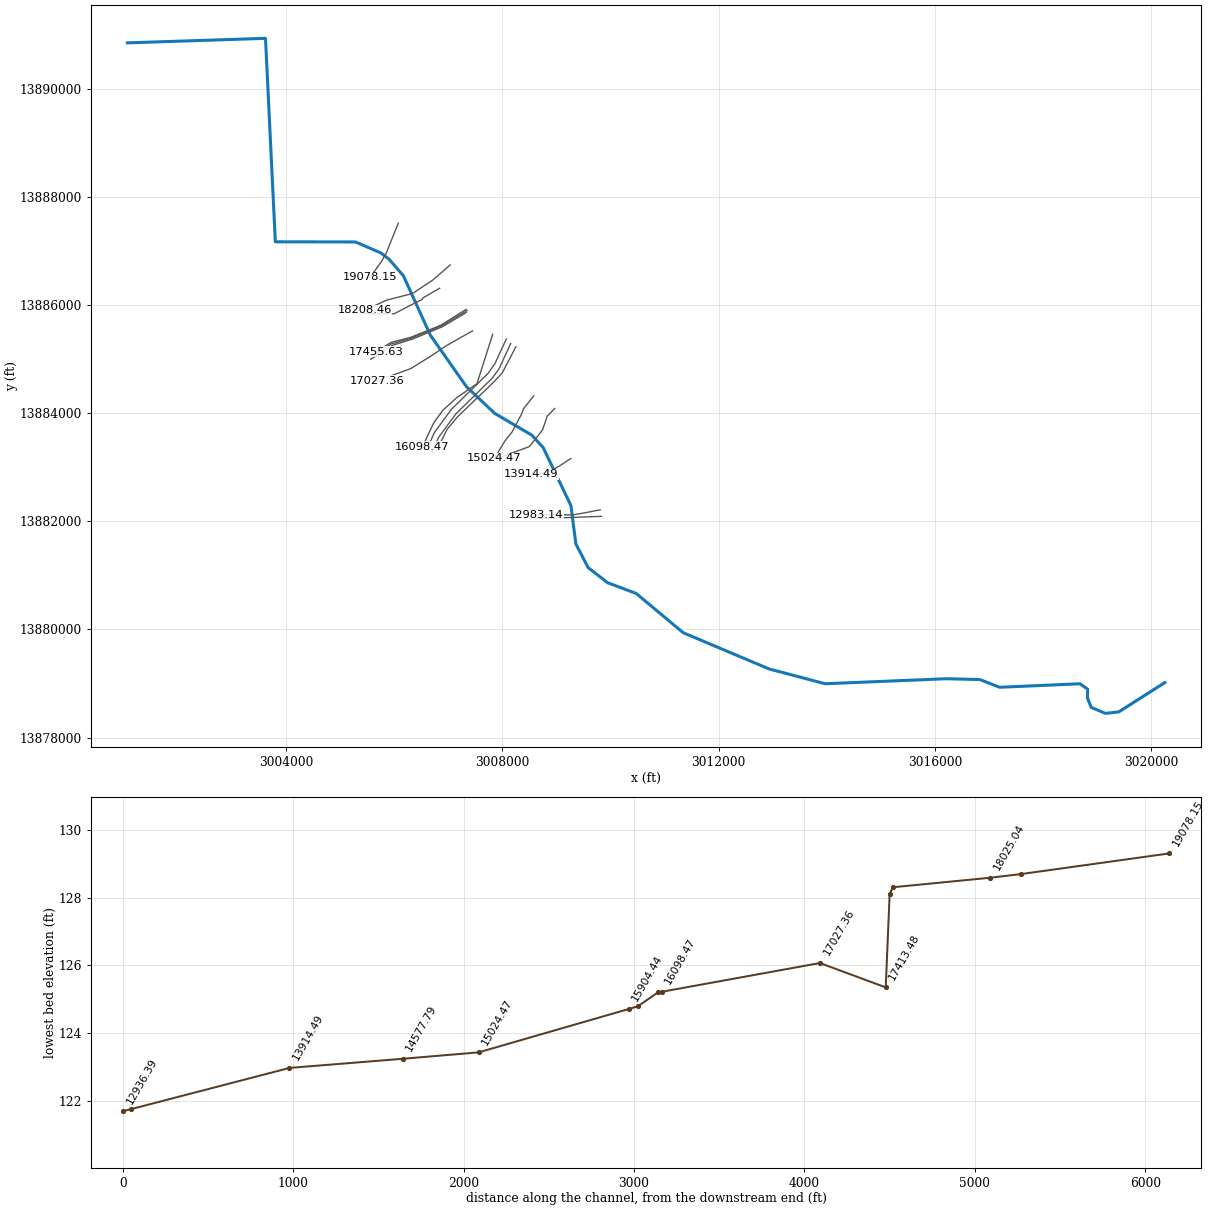
--- U120-00-00.prj (project) ---

Proj Title=U120-00-00 2019 (Re-Study)
Current Plan=p02
Default Exp/Contr=0.3,0.1
English Units
Geom File=g01
Flow File=f01
Flow File=f02
Flow File=f03
Plan File=p01
Plan File=p02
Plan File=p03
Y Axis Title=Elevation
X Axis Title(PF)=Main Channel Distance
X Axis Title(XS)=Station
BEGIN DESCRIPTION:
Dinner Creek (U120-00-00)
(Flood Hazard & Floodway) Model
10-, 2-, 1-, and 0.2% Events
Filename U120_00_00.prj
Prepared by:  LAN                               Date: 10/29/2012
Reviewed by: HCFCD                         Date: 10/18/2012
STATUS: Final
ADDICKS WATERSHED MODEL UPDATE
HARRIS COUNTY, TEXAS
END DESCRIPTION:
DSS Export Rating Curves= 0
DSS Export Rating Curve Sorted= 0
DSS Export Volume Flow Curves= 0
DXF OffsetX= 0
DXF OffsetY= 0
DXF ScaleX= 1
DXF ScaleY= 10

--- U120-00-00.p02 (plan) ---

Plan Title=Effective Floodway 2019 (Re-Study)
Program Version=4.10
Short Identifier=Eff+ReStudy FW
Geom File=g01
Flow File=f02
Subcritical Flow
K Sum by GR= 0
Std Step Tol= 0.01
Critical Tol= 0.01
Num of Std Step Trials= 20
Max Error Tol= 0.3
Flow Tol Ratio= 0.001
Split Flow NTrial= 30
Split Flow Tol= 0.02
Split Flow Ratio= 0.02
Log Output Level= 0
Friction Slope Method= 1
Unsteady Friction Slope Method= 2
Unsteady Bridges Friction Slope Method= 1
Parabolic Critical Depth
Global Vel Dist= 0 , 0 , 0
Global Log Level= 0
CheckData=True
Encroach Param=-1 ,0,0, 2
Encroach River=U120-00-00
Encroach Reach=U120-00-00_0003
Encroach Node=19078.15
       1  600.15  704.74
Encroach Node=18208.46
       1  844.71  938.36
Encroach Node=18025.04
       1  474.93  573.62
Encroach Node=17455.63
       1  753.95  850.62
Encroach Node=17436.38
       1  761.17  859.96
Encroach Node=17413.48
       1  731.51  831.31
Encroach Node=17027.36
       1  639.23     743
Encroach Node=16098.47
       1 1083.01 1192.34
Encroach Node=16076.21
       1 1124.99 1235.63
Encroach Node=15958.48
       1 1115.22 1249.89
Encroach Node=15904.44
       1 1134.97 1263.12
Encroach Node=15024.47
       1  590.88  715.04
Encroach Node=14577.79
       1  605.56  722.46
Encroach Node=13914.49
       1  303.32  435.27
Encroach Node=12983.14
       1  441.24  571.71
Encroach Node=12936.39
       1  471.52  568.95
Encroach Node=12881.45
       1  471.52  583.52
Encroach Node=12864.04
       1  461.66  602.95
Encroach Node=12848
       1   451.8  578.66
Encroach Node=12652.78
       1  474.66   610.1
Encroach Node=11780.53
       1  317.59  444.71
Encroach Node=11619.05
       1  295.86  418.79
Encroach Node=11542.75
       1  295.86  413.81
Encroach Node=11213.5
       1  408.94  538.07
Encroach Node=10937.51
       1   408.9  539.05
Encroach Node=10913.84
       1   408.9  539.05
Encroach Node=10473.05
       1  442.03  566.03
Encroach Node=9957.791
       1   407.2  542.03
Encroach Node=8902.806
       1  476.38  600.96
Encroach Node=8091.412
       1  381.99  501.69
Encroach Node=7994.904
       1     377  491.71
Encroach Node=7883.304
       1  393.99  542.57
Encroach Node=7745.163
       1  374.42  532.57
Encroach Node=7660.303
       1  372.94  522.12
Encroach Node=7542.502
       1  453.76  578.41
Encroach Node=7360.69
       1   539.9  663.54
Encroach Node=6817.104
       1   83.53  206.38
Encroach Node=5915.036
       1   83.88  207.22
Encroach Node=4916.15
       1  122.57  240.97
Encroach Node=3978.517
       1  274.07   392.7
Encroach Node=3608.501
       1  325.82  438.94
Encroach Node=3387.121
       1   308.3  415.81
Encroach Node=2871.229
       1  328.15  446.57
Encroach Node=2597.571
       1  472.65  584.45
Encroach Node=2407.601
       1  380.37  477.71
Encroach Node=2096.011
       1  239.42  353.77
Encroach Node=2013.345
       1  267.21   371.1
Encroach Node=1924.927
       1  289.02  408.61
Encroach Node=1622.732
       1  350.18  465.05
Encroach Node=1125.422
       1  270.35  359.44
Encroach Node=997.7322
       1     310     435
Encroach Node=948.8668
       1     310     440
Encroach Node=873.4696
       1  214.92  371.19
Encroach Node=783.011
       1  219.91  376.17
Encroach Node=736.1243
       1  226.89  365.54
Encroach Node=628.7742
       1   217.5  346.71
Encroach Node=534.5508
       1  149.85  279.06
Encroach Node=307.2545
       1  181.12  310.08
Computation Interval=1HOUR
Output Interval=1HOUR
Run HTab= 0
Run UNet= 0
Run PostProcess= 0
Run WQNet= 0
UNET Theta= 1
UNET Theta Warmup= 1
UNET ZTol= 0.02
UNET ZSATol= 0.05
UNET MxIter= 20
UNET MaxInSteps= 0
UNET DtIC= 0
UNET DtMin= 0
UNET MaxCRTS= 20
UNET WFStab= 2
UNET SFStab= 1
UNET WFX= 1
UNET SFX= 1
UNET DSS MLevel= 4
UNET DZMax Abort= 100
UNET Convert EG Bridges= 0
UNET Use Existing IB Tables=-1
UNET Froude Reduction=False
UNET Froude Limit= 1
UNET Froude Power= 10
UNET Time Slicing=0,0, 5
UNET Junction Losses=0
Instantaneous Interval=1HOUR
Write IC File= 0
Write IC File at Sim End=0
Echo Input=False
Echo Parameters=False
Echo Output=False
Write Detailed= 0
WQ AD Non Conservative
WQ ULTIMATE=-1
WQ Max Comp Step=1HOUR
WQ Output Interval=15MIN
WQ Output Selected Increments= 0
WQ Output face flow=0
WQ Output face velocity=0
WQ Output face area=0
WQ Output face dispersion=0
WQ Output cell volume=0
WQ Output cell surface area=0
WQ Output cell continuity=0
WQ Output cumulative cell continuity=0
WQ Output face conc=0
WQ Output face dconc_dx=0
WQ Output face courant=0
WQ Output face peclet=0
WQ Output face adv mass=0
WQ Output face disp mass=0
WQ Output cell mass=0
WQ Output cell source sink temp=0
WQ Output cell source sink nsm=0
WQ Output MaxMinRange=-1
WQ Daily Max Min Mean=-1
WQ Daily Range=0
WQ Daily Time=0
WQ Create Restart=0
WQ Fixed Restart=0
WQ System Summary=0
WQ Use Fixed Temperature=0
Sorting and Armoring Iterations= 10
XS Update Threshold= 0.02
Hydraulics Update Threshold= 0.02
Energy Slope Method= 1
Volume Change Method= 0
XS Weighting Method= 0
Number of US Weighted Cross Sections= 1
Number of DS Weighted Cross Sections= 1
Upstream XS Weight=0.25
Main XS Weight=0.5
Downstream XS Weight=0.25
Number of DS XS's Weighted with US Boundary= 1
Upstream Boundary Weight= 1
Weight of XSs Associated with US Boundary= 0
Number of US XS's Weighted with DS Boundary= 1
Downstream Boundary Weight= 0.5
Weight of XSs Associated with DS Boundary= 0.5
Sediment Output Level= 4
Mass or Volume Output= 0
Output Increment Type= 1
Profile and TS Output Increment= 10
XS Output Flag= 0
XS Output Increment= 10
Disregard all LS=0
Disregard all Conn=0
Disregard all Breaches=0
Disregard all Pumps=0

--- U120-00-00.p01 (plan) ---

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Plan Title=Effective Multi-Profile 2019 (Re-Study)
Short Identifier=Eff+ReStudy MP
Geom File=g01
Flow File=f01
Calc Critical at every XS
Encroach Param=-1 ,0,0, 0

--- U120-00-00.p03 (plan) ---

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Plan Title=Conveyance (CO)
Short Identifier=CO
Geom File=g01
Flow File=f03
Encroach Param=-1 ,0,0, 0

--- U120-00-00.f02 (steady flow) ---

Flow Title=Effective Floodway 2019
Program Version=4.10
Number of Profiles= 2
Profile Names=100YR,FW
River Rch & RM=U120-00-00,U120-00-00_0003 ,19078.15
     845     845
River Rch & RM=U120-00-00,U120-00-00_0003 ,18208.46
     880     880
River Rch & RM=U120-00-00,U120-00-00_0003 ,17455.63
     902     902
River Rch & RM=U120-00-00,U120-00-00_0003 ,17027.36
     949     949
River Rch & RM=U120-00-00,U120-00-00_0003 ,16098.47
     959     959
River Rch & RM=U120-00-00,U120-00-00_0003 ,15904.44
    1007    1007
River Rch & RM=U120-00-00,U120-00-00_0003 ,15024.47
    1032    1032
River Rch & RM=U120-00-00,U120-00-00_0003 ,14577.79
    1071    1071
River Rch & RM=U120-00-00,U120-00-00_0003 ,13914.49
    1127    1127
River Rch & RM=U120-00-00,U120-00-00_0003 ,12983.14
    1148    1148
River Rch & RM=U120-00-00,U120-00-00_0003 ,12652.78
    1205    1205
River Rch & RM=U120-00-00,U120-00-00_0003 ,11780.53
    1262    1262
River Rch & RM=U120-00-00,U120-00-00_0003 ,10937.51
    1295    1295
River Rch & RM=U120-00-00,U120-00-00_0003 ,10473.05
    1332    1332
River Rch & RM=U120-00-00,U120-00-00_0003 ,9957.791
    1412    1412
River Rch & RM=U120-00-00,U120-00-00_0003 ,8902.806
    1477    1477
River Rch & RM=U120-00-00,U120-00-00_0003 ,8091.412
    1538    1538
River Rch & RM=U120-00-00,U120-00-00_0003 ,7360.69
    1584    1584
River Rch & RM=U120-00-00,U120-00-00_0003 ,6817.104
    1665    1665
River Rch & RM=U120-00-00,U120-00-00_0003 ,5915.036
    1760    1760
River Rch & RM=U120-00-00,U120-00-00_0003 ,4916.15
    1853    1853
River Rch & RM=U120-00-00,U120-00-00_0003 ,3978.517
    1915    1915
River Rch & RM=U120-00-00,U120-00-00_0003 ,3387.121
    2000    2000
River Rch & RM=U120-00-00,U120-00-00_0003 ,2597.571
    2076    2076
River Rch & RM=U120-00-00,U120-00-00_0003 ,1924.927
    2170    2170
River Rch & RM=U120-00-00,U120-00-00_0003 ,1125.422
    2270    2270
Boundary for River Rch & Prof#=U120-00-00,U120-00-00_0003 , 1
Up Type= 0
Dn Type= 3
Dn Slope=0.0048
Boundary for River Rch & Prof#=U120-00-00,U120-00-00_0003 , 2
Up Type= 0
Dn Type= 3
Dn Slope=0.0048
Observed WS=U120-00-00      ,U120-00-00_0003 ,19078.15,0,133.95,135.38
Observed WS=U120-00-00      ,U120-00-00_0003 ,18208.46,0,133.48,134.92
Observed WS=U120-00-00      ,U120-00-00_0003 ,18025.04,0,133.4,134.84
Observed WS=U120-00-00      ,U120-00-00_0003 ,17455.63,0,133.1,134.55
Observed WS=U120-00-00      ,U120-00-00_0003 ,17436.38,0,133.09,134.54
Observed WS=U120-00-00      ,U120-00-00_0003 ,17413.48,0,133.09,134.54
Observed WS=U120-00-00      ,U120-00-00_0003 ,17027.36,0,132.96,134.4
Observed WS=U120-00-00      ,U120-00-00_0003 ,16098.47,0,132.88,134.31
Observed WS=U120-00-00      ,U120-00-00_0003 ,16076.21,0,132.81,134.17
Observed WS=U120-00-00      ,U120-00-00_0003 ,15958.48,0,132.61,133.75
Observed WS=U120-00-00      ,U120-00-00_0003 ,15904.44,0,132.6,133.74
Observed WS=U120-00-00      ,U120-00-00_0003 ,15024.47,0,132.43,133.49
Observed WS=U120-00-00      ,U120-00-00_0003 ,14577.79,0,132.38,133.39
Observed WS=U120-00-00      ,U120-00-00_0003 ,13914.49,0,132.31,133.28
Observed WS=U120-00-00      ,U120-00-00_0003 ,12983.14,0,132.17,133.02
Observed WS=U120-00-00      ,U120-00-00_0003 ,12936.39,0,132.17,133.01
Observed WS=U120-00-00      ,U120-00-00_0003 ,12881.45,0,132.06,132.88
Observed WS=U120-00-00      ,U120-00-00_0003 ,12864.04,0,132.06,132.89
Observed WS=U120-00-00      ,U120-00-00_0003 ,12848   ,0,131.88,132.86
Observed WS=U120-00-00      ,U120-00-00_0003 ,12652.78,0,131.86,132.85
Observed WS=U120-00-00      ,U120-00-00_0003 ,11780.53,0,131.84,132.78
Observed WS=U120-00-00      ,U120-00-00_0003 ,11619.05,0,131.83,132.76
Observed WS=U120-00-00      ,U120-00-00_0003 ,11542.75,0,127.21,128.91
Observed WS=U120-00-00      ,U120-00-00_0003 ,11213.5 ,0,127.08,128.78
Observed WS=U120-00-00      ,U120-00-00_0003 ,10937.51,0,126.89,128.58
Observed WS=U120-00-00      ,U120-00-00_0003 ,10913.84,0,126.86,128.54
Observed WS=U120-00-00      ,U120-00-00_0003 ,10473.05,0,126.61,128.28
Observed WS=U120-00-00      ,U120-00-00_0003 ,9957.791,0,126.36,128.01
Observed WS=U120-00-00      ,U120-00-00_0003 ,8902.806,0,125.84,127.49
Observed WS=U120-00-00      ,U120-00-00_0003 ,8091.412,0,125.31,126.99
Observed WS=U120-00-00      ,U120-00-00_0003 ,7994.904,0,125.24,126.93
Observed WS=U120-00-00      ,U120-00-00_0003 ,7883.304,0,125.17,126.86
Observed WS=U120-00-00      ,U120-00-00_0003 ,7745.163,0,125.09,126.78
Observed WS=U120-00-00      ,U120-00-00_0003 ,7660.303,0,125.04,126.74
Observed WS=U120-00-00      ,U120-00-00_0003 ,7542.502,0,124.97,126.67
Observed WS=U120-00-00      ,U120-00-00_0003 ,7360.69 ,0,124.86,126.57
Observed WS=U120-00-00      ,U120-00-00_0003 ,6817.104,0,124.54,126.22
Observed WS=U120-00-00      ,U120-00-00_0003 ,5915.036,0,123.86,125.51
Observed WS=U120-00-00      ,U120-00-00_0003 ,4916.15 ,0,123.08,124.72
Observed WS=U120-00-00      ,U120-00-00_0003 ,3978.517,0,122.38,123.97
Observed WS=U120-00-00      ,U120-00-00_0003 ,3608.501,0,121.76,123.26
Observed WS=U120-00-00      ,U120-00-00_0003 ,3387.121,0,121.07,122.53
Observed WS=U120-00-00      ,U120-00-00_0003 ,2871.229,0,118.91,120.38
Observed WS=U120-00-00      ,U120-00-00_0003 ,2597.571,0,117.85,119.44
Observed WS=U120-00-00      ,U120-00-00_0003 ,2407.601,0,116.88,118.53
Observed WS=U120-00-00      ,U120-00-00_0003 ,2096.011,0,115.41,117.2
Observed WS=U120-00-00      ,U120-00-00_0003 ,2013.345,0,114.54,116.37
Observed WS=U120-00-00      ,U120-00-00_0003 ,1924.927,0,114.43,116.27
Observed WS=U120-00-00      ,U120-00-00_0003 ,1622.732,0,114.05,115.94
Observed WS=U120-00-00      ,U120-00-00_0003 ,1125.422,0,113.68,115.56
Observed WS=U120-00-00      ,U120-00-00_0003 ,997.7322,0,113.59,115.46
Observed WS=U120-00-00      ,U120-00-00_0003 ,948.8668,0,113.49,115.33
Observed WS=U120-00-00      ,U120-00-00_0003 ,873.4696,0,113.34,115.14
Observed WS=U120-00-00      ,U120-00-00_0003 ,783.011 ,0,113.05,114.79
Observed WS=U120-00-00      ,U120-00-00_0003 ,736.1243,0,112.9,114.62
Observed WS=U120-00-00      ,U120-00-00_0003 ,628.7742,0,112.56,114.25
Observed WS=U120-00-00      ,U120-00-00_0003 ,534.5508,0,112.27,113.91
Observed WS=U120-00-00      ,U120-00-00_0003 ,307.2545,0,111.55,113.11
DSS Import GetInterval= 0
DSS Import GetPeak= 0
DSS Import FillOption= 0

--- U120-00-00.f01 (steady flow) ---

Flow Title=Effective Multi-Profile 2019
Program Version=4.10
Number of Profiles= 4
Profile Names=10YR,50YR,100YR,500YR
River Rch & RM=U120-00-00,U120-00-00_0003 ,19078.15
     451     708     845    1245
River Rch & RM=U120-00-00,U120-00-00_0003 ,18208.46
     470     738     880    1298
River Rch & RM=U120-00-00,U120-00-00_0003 ,17455.63
     482     756     902    1329
River Rch & RM=U120-00-00,U120-00-00_0003 ,17027.36
     507     796     949    1399
River Rch & RM=U120-00-00,U120-00-00_0003 ,16098.47
     512     804     959    1415
River Rch & RM=U120-00-00,U120-00-00_0003 ,15904.44
     538     844    1007    1485
River Rch & RM=U120-00-00,U120-00-00_0003 ,15024.47
     551     866    1032    1522
River Rch & RM=U120-00-00,U120-00-00_0003 ,14577.79
     572     898    1071    1579
River Rch & RM=U120-00-00,U120-00-00_0003 ,13914.49
     602     945    1127    1662
River Rch & RM=U120-00-00,U120-00-00_0003 ,12983.14
     613     963    1148    1693
River Rch & RM=U120-00-00,U120-00-00_0003 ,12652.78
     643    1010    1205    1777
River Rch & RM=U120-00-00,U120-00-00_0003 ,11780.53
     674    1058    1262    1861
River Rch & RM=U120-00-00,U120-00-00_0003 ,10937.51
     692    1086    1295    1910
River Rch & RM=U120-00-00,U120-00-00_0003 ,10473.05
     712    1117    1332    1965
River Rch & RM=U120-00-00,U120-00-00_0003 ,9957.791
     754    1184    1412    2083
River Rch & RM=U120-00-00,U120-00-00_0003 ,8902.806
     789    1239    1477    2179
River Rch & RM=U120-00-00,U120-00-00_0003 ,8091.412
     821    1290    1538    2268
River Rch & RM=U120-00-00,U120-00-00_0003 ,7360.69
     846    1329    1584    2337
River Rch & RM=U120-00-00,U120-00-00_0003 ,6817.104
     890    1397    1665    2457
River Rch & RM=U120-00-00,U120-00-00_0003 ,5915.036
     940    1476    1760    2596
River Rch & RM=U120-00-00,U120-00-00_0003 ,4916.15
     990    1555    1853    2735
River Rch & RM=U120-00-00,U120-00-00_0003 ,3978.517
    1023    1607    1915    2825
River Rch & RM=U120-00-00,U120-00-00_0003 ,3387.121
    1068    1678    2000    2951
River Rch & RM=U120-00-00,U120-00-00_0003 ,2597.571
    1109    1742    2076    3063
River Rch & RM=U120-00-00,U120-00-00_0003 ,1924.927
    1159    1820    2170    3202
River Rch & RM=U120-00-00,U120-00-00_0003 ,1125.422
    1213    1905    2270    3350
Boundary for River Rch & Prof#=U120-00-00,U120-00-00_0003 , 1
Up Type= 0
Dn Type= 3
Dn Slope=0.0048
Boundary for River Rch & Prof#=U120-00-00,U120-00-00_0003 , 2
Up Type= 0
Dn Type= 3
Dn Slope=0.0048
Boundary for River Rch & Prof#=U120-00-00,U120-00-00_0003 , 3
Up Type= 0
Dn Type= 3
Dn Slope=0.0048
Boundary for River Rch & Prof#=U120-00-00,U120-00-00_0003 , 4
Up Type= 0
Dn Type= 3
Dn Slope=0.0048
Observed WS=U120-00-00      ,U120-00-00_0003 ,19078.15,0,133.95,135.38,136.05,138.03
Observed WS=U120-00-00      ,U120-00-00_0003 ,18208.46,0,133.48,134.92,135.61,137.7
Observed WS=U120-00-00      ,U120-00-00_0003 ,18025.04,0,133.4,134.84,135.54,137.64
Observed WS=U120-00-00      ,U120-00-00_0003 ,17455.63,0,133.1,134.55,135.26,137.44
Observed WS=U120-00-00      ,U120-00-00_0003 ,17436.38,0,133.09,134.54,135.25,137.44
Observed WS=U120-00-00      ,U120-00-00_0003 ,17413.48,0,133.09,134.54,135.25,137.43
Observed WS=U120-00-00      ,U120-00-00_0003 ,17027.36,0,132.96,134.4,135.13,137.34
Observed WS=U120-00-00      ,U120-00-00_0003 ,16098.47,0,132.88,134.31,135.04,137.27
Observed WS=U120-00-00      ,U120-00-00_0003 ,16076.21,0,132.81,134.17,134.85,136.99
Observed WS=U120-00-00      ,U120-00-00_0003 ,15958.48,0,132.61,133.75,134.31,135.69
Observed WS=U120-00-00      ,U120-00-00_0003 ,15904.44,0,132.6,133.74,134.3,135.7
Observed WS=U120-00-00      ,U120-00-00_0003 ,15024.47,0,132.43,133.49,134.02,135.33
Observed WS=U120-00-00      ,U120-00-00_0003 ,14577.79,0,132.38,133.39,133.92,135.21
Observed WS=U120-00-00      ,U120-00-00_0003 ,13914.49,0,132.31,133.28,133.79,135.03
Observed WS=U120-00-00      ,U120-00-00_0003 ,12983.14,0,132.17,133.02,133.48,134.55
Observed WS=U120-00-00      ,U120-00-00_0003 ,12936.39,0,132.17,133.01,133.45,134.52
Observed WS=U120-00-00      ,U120-00-00_0003 ,12881.45,0,132.06,132.88,133.32,134.35
Observed WS=U120-00-00      ,U120-00-00_0003 ,12864.04,0,132.06,132.89,133.34,134.39
Observed WS=U120-00-00      ,U120-00-00_0003 ,12848   ,0,131.88,132.86,133.28,134.31
Observed WS=U120-00-00      ,U120-00-00_0003 ,12652.78,0,131.86,132.85,133.27,134.28
Observed WS=U120-00-00      ,U120-00-00_0003 ,11780.53,0,131.84,132.78,133.19,134.15
Observed WS=U120-00-00      ,U120-00-00_0003 ,11619.05,0,131.83,132.76,133.16,134.11
Observed WS=U120-00-00      ,U120-00-00_0003 ,11542.75,0,127.21,128.91,129.67,131.66
Observed WS=U120-00-00      ,U120-00-00_0003 ,11213.5 ,0,127.08,128.78,129.54,131.55
Observed WS=U120-00-00      ,U120-00-00_0003 ,10937.51,0,126.89,128.58,129.33,131.34
Observed WS=U120-00-00      ,U120-00-00_0003 ,10913.84,0,126.86,128.54,129.3,131.21
Observed WS=U120-00-00      ,U120-00-00_0003 ,10473.05,0,126.61,128.28,129.04,130.94
Observed WS=U120-00-00      ,U120-00-00_0003 ,9957.791,0,126.36,128.01,128.76,130.66
Observed WS=U120-00-00      ,U120-00-00_0003 ,8902.806,0,125.84,127.49,128.24,130.12
Observed WS=U120-00-00      ,U120-00-00_0003 ,8091.412,0,125.31,126.99,127.75,129.65
Observed WS=U120-00-00      ,U120-00-00_0003 ,7994.904,0,125.24,126.93,127.69,129.59
Observed WS=U120-00-00      ,U120-00-00_0003 ,7883.304,0,125.17,126.86,127.62,129.53
Observed WS=U120-00-00      ,U120-00-00_0003 ,7745.163,0,125.09,126.78,127.55,129.45
Observed WS=U120-00-00      ,U120-00-00_0003 ,7660.303,0,125.04,126.74,127.5,129.41
Observed WS=U120-00-00      ,U120-00-00_0003 ,7542.502,0,124.97,126.67,127.44,129.34
Observed WS=U120-00-00      ,U120-00-00_0003 ,7360.69 ,0,124.86,126.57,127.34,129.24
Observed WS=U120-00-00      ,U120-00-00_0003 ,6817.104,0,124.54,126.22,126.97,128.84
Observed WS=U120-00-00      ,U120-00-00_0003 ,5915.036,0,123.86,125.51,126.25,128.07
Observed WS=U120-00-00      ,U120-00-00_0003 ,4916.15 ,0,123.08,124.72,125.44,127.22
Observed WS=U120-00-00      ,U120-00-00_0003 ,3978.517,0,122.38,123.97,124.66,126.38
Observed WS=U120-00-00      ,U120-00-00_0003 ,3608.501,0,121.76,123.26,123.92,125.56
Observed WS=U120-00-00      ,U120-00-00_0003 ,3387.121,0,121.07,122.53,123.19,124.79
Observed WS=U120-00-00      ,U120-00-00_0003 ,2871.229,0,118.91,120.38,121.04,122.59
Observed WS=U120-00-00      ,U120-00-00_0003 ,2597.571,0,117.85,119.44,120.13,121.79
Observed WS=U120-00-00      ,U120-00-00_0003 ,2407.601,0,116.88,118.53,119.25,121.01
Observed WS=U120-00-00      ,U120-00-00_0003 ,2096.011,0,115.41,117.2,117.98,119.88
Observed WS=U120-00-00      ,U120-00-00_0003 ,2013.345,0,114.54,116.37,117.16,119.09
Observed WS=U120-00-00      ,U120-00-00_0003 ,1924.927,0,114.43,116.27,117.07,119.01
Observed WS=U120-00-00      ,U120-00-00_0003 ,1622.732,0,114.05,115.94,116.75,118.72
Observed WS=U120-00-00      ,U120-00-00_0003 ,1125.422,0,113.68,115.56,116.36,118.31
Observed WS=U120-00-00      ,U120-00-00_0003 ,997.7322,0,113.59,115.46,116.26,118.21
Observed WS=U120-00-00      ,U120-00-00_0003 ,948.8668,0,113.49,115.33,116.12,118.04
Observed WS=U120-00-00      ,U120-00-00_0003 ,873.4696,0,113.34,115.14,115.9,117.77
Observed WS=U120-00-00      ,U120-00-00_0003 ,783.011 ,0,113.05,114.79,115.53,117.34
Observed WS=U120-00-00      ,U120-00-00_0003 ,736.1243,0,112.9,114.62,115.36,117.15
Observed WS=U120-00-00      ,U120-00-00_0003 ,628.7742,0,112.56,114.25,114.96,116.72
Observed WS=U120-00-00      ,U120-00-00_0003 ,534.5508,0,112.27,113.91,114.62,116.34
Observed WS=U120-00-00      ,U120-00-00_0003 ,307.2545,0,111.55,113.11,113.78,115.42
DSS Import GetInterval= 0
DSS Import GetPeak= 0
DSS Import FillOption= 0

--- U120-00-00.f03 (steady flow) ---

Flow Title=Conveyance Flows
Program Version=4.10
Number of Profiles= 1
Profile Names=100YR_CO
River Rch & RM=U120-00-00,U120-00-00_0003 ,19078.15
    4200
Boundary for River Rch & Prof#=U120-00-00,U120-00-00_0003 , 1
Up Type= 0
Dn Type= 3
Dn Slope=0.0048
DSS Import GetInterval= 0
DSS Import GetPeak= 0
DSS Import FillOption= 0

--- U120-00-00.g01 (geometry) ---

Geom Title=U120-00-00 2019 (Re-Study)
Program Version=4.10

River Reach=U120-00-00      ,U120-00-00_0003
Reach XY= 30
3001067.3917468613890847.3493804 3003621.771808713890931.1953413
3003803.8567463613887168.94039873005287.7448546913887165.4472954
3005757.8958172813886961.51430443005909.4844248613886843.1579138
3006171.4816042813886541.73758493006671.3677436113885439.8326364
3007338.3385225213884489.78401163007861.99003428 13883994.570107
3008545.1599277713883595.10535483008755.6887061913883365.4129008
3009269.6578226113882290.92325193009361.4568516213881581.5837913
3009587.7109922813881143.98427283009947.6495768613880864.4658029
3010476.9385445313880665.93667243011345.9253236113879939.9279539
3012933.92542845 13879269.9456983013970.7816224413878996.0620594
3016213.1032532813879088.75872443016831.08659735  13879073.51302
3017199.4434721913878930.75936853018684.11241886 13878995.745459
3018826.8660703613878894.10852323018821.3221181913878734.5694722
3018890.6202079513878559.16857633019154.4142997713878447.9840873
 3019400.344582213878475.2412507 3020253.502324713879018.0016481

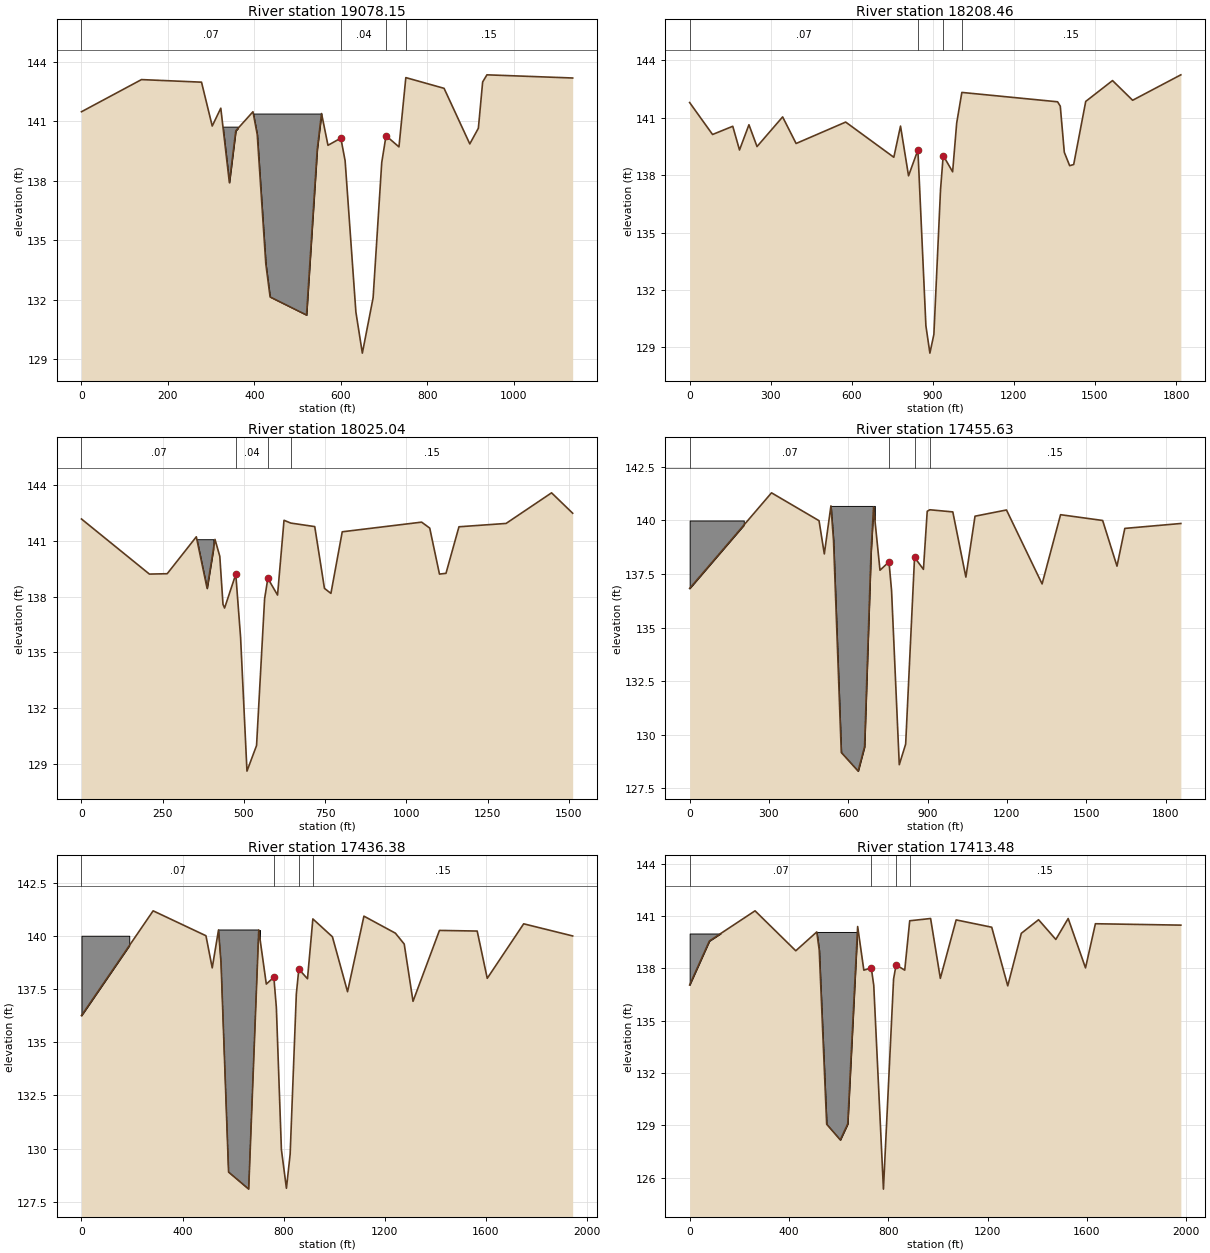
Type RM Length L Ch R = 1 ,19078.15,895.46,869.69,844.93
Node Name=S
XS GIS Cut Line= 4
3006079.00016195 13887515.0000743005847.9999677813886944.9999017
3005765.0001337813886802.99985763005557.9998916113886512.0001115
#Sta/Elev= 30
       0  141.47  138.88  143.09  277.76  142.96  302.55  140.75  322.39  141.65
  342.23   137.9  357.11  140.51  396.79  141.47  406.71  140.32  426.55  133.81
  436.47  132.14  520.79  131.23  545.59  139.58  555.51  141.38  570.39  139.78
  600.15  140.14  610.07     139  634.97  131.38  649.92  129.31  674.84   132.1
  694.78  138.91  704.74  140.26  734.65   139.7  750.54  143.19  839.03  142.65
  898.55  139.85  918.39  140.64   928.3  142.97  938.22  143.33 1136.62  143.17
#Mann= 4 ,-1 , 0
       0     .07       0  600.15     .04       0  704.74     .07       0
  750.54     .15       0
#Block Obstruct= 2 ,-1
  317.43  362.07  140.72  396.79  555.51  141.38
Bank Sta=600.15,704.74
XS Rating Curve= 0 ,0
Exp/Cntr=0.3,0.1

Type RM Length L Ch R = 1 ,18208.46,180.14,183.43,187.56
XS GIS Cut Line= 6
3007037.9998843713886740.99998163006709.9998841913886456.9998934
3006358.9999300213886225.00002943006285.0000780213886198.0000834
3005869.9999237813886091.99996733005454.0000996113885905.0000132
#Sta/Elev= 30
       0   141.8   84.78  140.13  159.58  140.56  184.52  139.32  219.43  140.64
  249.35   139.5   344.1  141.05  393.97  139.66  577.41  140.78  755.61  138.94
  780.36  140.57  810.06  137.97  844.71  139.32   874.3  130.13  889.07   128.7
  903.84  129.68  928.46  137.25  938.36  139.03  973.23  138.18  988.17  140.72
  1007.3  142.33  1361.7  141.84 1371.62  141.61 1386.49   139.2 1406.32   138.5
  1421.2  138.56 1465.81  141.86 1564.96  142.95 1639.33  141.92  1817.8  143.25
#Mann= 4 ,-1 , 0
       0     .07       0  844.71     .04       0  938.36     .07       0
  1007.3     .15       0
Bank Sta=844.71,938.36
XS Rating Curve= 0 ,0
Exp/Cntr=0.3,0.1

Type RM Length L Ch R = 1 ,18025.04,564.02,569.4,558.01
XS GIS Cut Line= 6
3006842.9999462813886310.9998574 3006528.999918113886127.9998953
3006518.9999381213886101.99994733006376.9998940213886034.0000833
3006001.9999878613885838.00014723005462.0000836113885838.0001472
#Sta/Elev= 30
       0  142.18   209.1  139.21  263.86  139.23  353.48  141.22  386.65  138.44
  410.97  141.08  425.73  140.17  435.57  137.58  440.49  137.38  474.93   139.2
  489.69  135.81  509.37  128.59  538.89  129.97  563.67  137.88  573.62  138.98
  603.49  138.08   623.4  142.11  644.26  141.96  717.99  141.77  747.86  138.44
  767.77  138.17  802.61  141.49 1046.87  142.01 1071.87  141.69 1101.87  139.21
 1121.87  139.25 1161.87  141.76 1306.87  141.94 1446.87  143.59 1511.87  142.49
#Mann= 4 ,-1 , 0
       0     .07       0  474.93     .04       0  573.62     .07       0
  644.26     .15       0
#Block Obstruct= 1 ,-1
  353.48  406.05  141.09
Bank Sta=474.93,573.62
XS Rating Curve= 0 ,0
Exp/Cntr=0.3,0.1

Type RM Length L Ch R = 1 ,17455.63,17.91,19.25,19.42
Node Name=R
XS GIS Cut Line= 6
3007330.7909654413885918.70077323006877.99987628 13885634.999897
3006784.00006428 13885592.9999813006300.0000480313885400.0000389
3005942.6736629513885307.31977813005662.0042767813885133.2613992
#Sta/Elev= 30
       0  136.83  309.61  141.29  489.38  139.99  509.36  138.44  534.33  140.68
  544.13  139.07  573.55  129.18  637.28  128.31  661.59  129.45  685.89  138.47
  695.62  140.63  719.92  137.68  753.95  138.07  763.67  136.73  792.84  128.61
  816.98  129.57  850.62  138.28  884.22  137.72  898.53  140.43  908.46   140.5
  995.31   140.4 1044.73  137.36 1079.32   140.2  1198.3  140.49 1332.99  137.04
 1402.83  140.27 1562.05     140 1616.27  137.87 1645.84  139.63  1857.8  139.86
#Mann= 4 ,-1 , 0
       0     .07       0  753.95     .04       0  850.62     .07       0
  908.46     .15       0
#Block Obstruct= 2 ,-1
       0  204.74     140  534.33  700.48  140.68
Bank Sta=753.95,850.62
XS Rating Curve= 0 ,0
Exp/Cntr=0.3,0.1

Type RM Length L Ch R = 1 ,17436.38,21.99,22.9,22.26
XS GIS Cut Line= 6
 3007350.372291113885896.94327083006885.99986027 13885616.999933
3006637.00003019 13885516.0001353006312.0000240213885382.0000749
3005942.6736629513885279.03538583005609.7865334513885061.4620021
#Sta/Elev= 30
       0  136.25  283.55  141.17  492.48     140  517.35  138.49  542.23  140.27
  552.18  138.73  582.04   128.9  661.65   128.1  701.46  140.27  731.32  137.73
  761.17  138.05  771.12  136.63  791.03  129.96  810.93  128.14  825.64  129.74
  850.15  137.27  859.96  138.43  894.28  137.98  915.53  140.79  992.92  139.95
 1052.76  137.37 1117.59  140.92 1242.14  140.12    1277  139.61 1311.85  136.92
 1416.42  140.25 1565.77  140.22 1605.53     138 1749.69  140.56 1943.56  139.99
#Mann= 4 ,-1 , 0
       0     .07       0  761.17     .04       0  859.96     .07       0
  915.53     .15       0
#Block Obstruct= 2 ,-1
       0  189.03     140  542.23  706.44  140.27
Bank Sta=761.17,859.96
XS Rating Curve= 0 ,0
Exp/Cntr=0.3,0.1

Type RM Length L Ch R = 1 ,17413.48,378.15,386.12,392.84
XS GIS Cut Line= 6
 3007335.142334713885862.13166063006895.99984027 13885598.999969
3006503.9999681113885436.99996493006322.0000040213885364.0001109
3005966.6066859413885252.92651423005568.44770536 13884996.190151
#Sta/Elev= 30
       0  137.05   79.53  139.57  263.43   141.3  427.45  139.01  511.94  140.09
  521.92  139.05  551.86  129.07  606.75  128.17  636.69  129.09  676.62   140.4
  701.57   137.9  731.51  138.03  741.49  137.03  780.47  125.35  821.33  137.39
  831.31   138.2  866.24   137.9  886.32  140.73  970.42  140.86 1009.64  137.43
 1073.37  140.78 1216.59  140.36 1281.13     137 1335.74  140.01 1405.25  140.79
 1474.75  139.66 1524.49  140.86 1594.31  138.03  1634.2  140.56  1978.3  140.48
#Mann= 4 ,-1 , 0
       0     .07       0  731.51     .04       0  831.31     .07       0
  886.32     .15       0
#Block Obstruct= 2 ,-1
       0   134.2     140  511.94  676.62  140.09
Bank Sta=731.51,831.31
XS Rating Curve= 0 ,0
Exp/Cntr=0.3,0.1

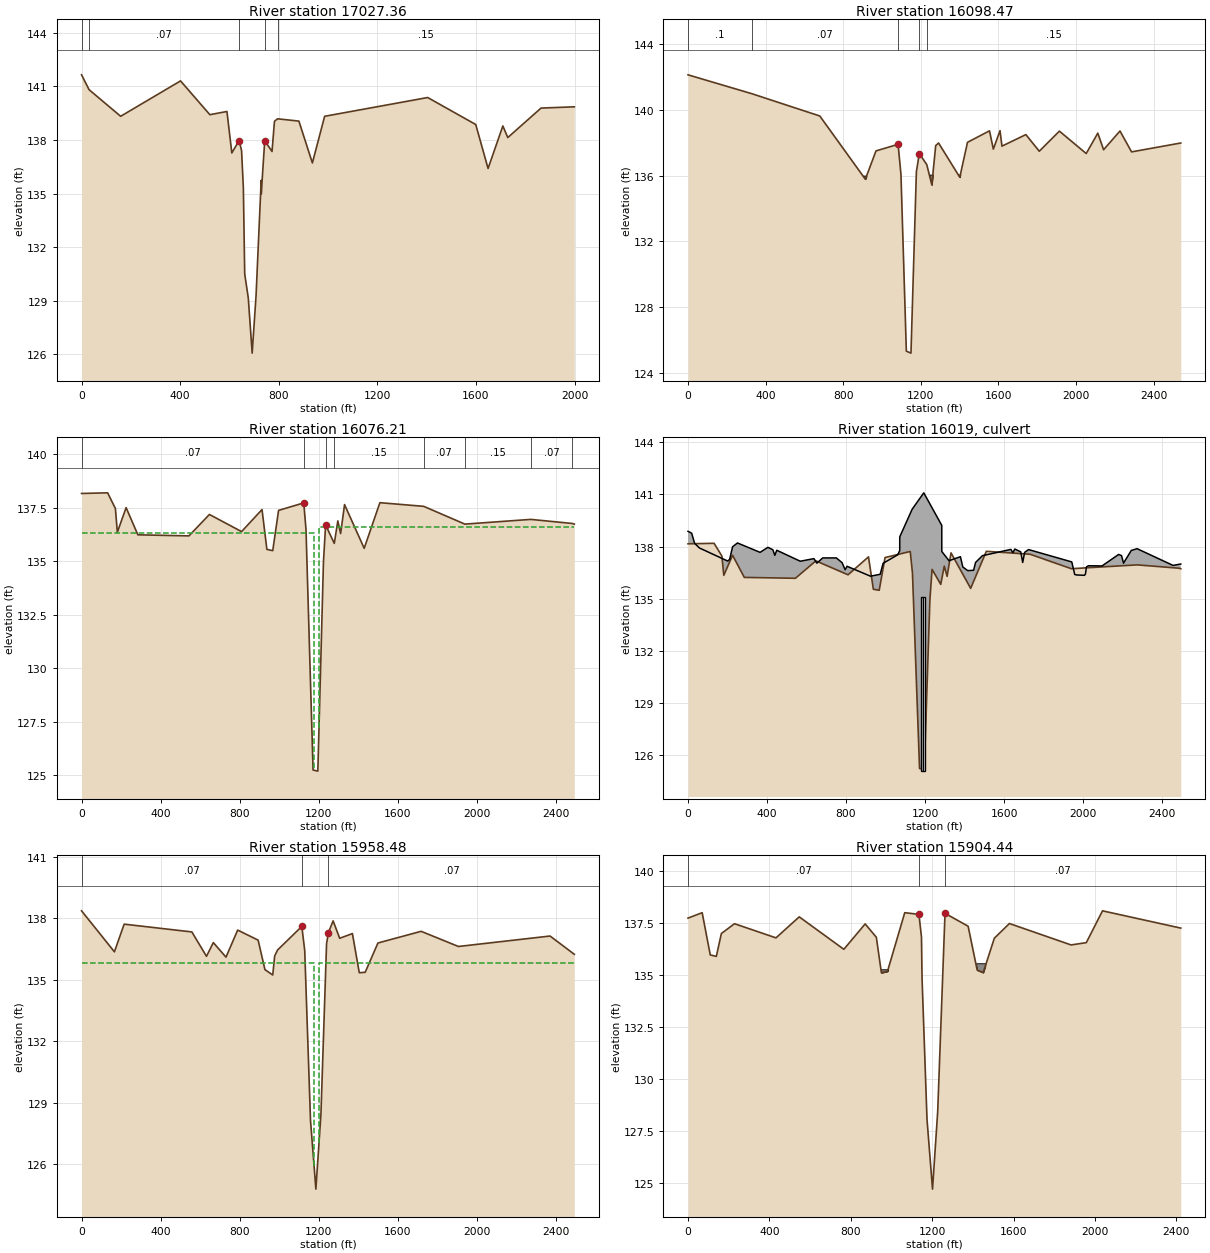
Type RM Length L Ch R = 1 ,17027.36,923.33,928.89,931.15
XS GIS Cut Line= 5
3007450.00004461 13885521.0001253006958.0000443613885243.0000249
3006738.0001562813885091.99999883006312.0000240213884825.9998746
3005687.9999596913884597.0000045
#Sta/Elev= 30
       0  141.64   30.46  140.81  158.63  139.32  401.52   141.3   520.5  139.41
  589.82  139.59  609.58  137.27  639.23  137.96  649.11   137.4  656.41   135.3
  661.84   130.5  676.35  129.16  692.12  126.07  707.85  129.28  728.65  135.73
  728.93  134.98     743  137.96  772.65  137.35  782.53  139.04   795.1  139.18
  881.67  139.05  936.37  136.71  986.09  139.32 1404.14  140.37 1599.05  138.86
 1649.03   136.4    1709  138.78 1728.99  138.13 1863.93  139.78 1998.86  139.85
#Mann= 5 ,-1 , 0
       0      .1       0   30.46     .07       0  639.23     .04       0
     743     .07       0   795.1     .15       0
Bank Sta=639.23,743
XS Rating Curve= 0 ,0
Exp/Cntr=0.3,0.1

Type RM Length L Ch R = 1 ,16098.47,22.17,22.26,27.19
Node Name=Q
XS GIS Cut Line= 6
3007822.9999547813885458.99992093007531.9998806113884545.0001085
3007155.9999764413884283.99997443006900.0001603713884052.0001103
3006735.0001622713883823.99991013006523.9999281213883379.0001439
#Sta/Elev= 30
       0  142.12  329.96  140.97  679.44  139.62  914.24  135.78  969.11   137.5
 1083.01   137.9 1097.87  136.07 1125.61  125.34 1149.42  125.22 1177.38  136.23
 1192.34  137.34 1230.86  136.67 1257.01  135.44  1276.9  137.82 1291.81  137.98
 1401.18   135.9 1440.81  138.02 1554.33  138.72 1574.07  137.61 1608.62  138.73
 1618.49  137.79 1741.88  138.49    1811  137.48 1914.68   138.7 2052.97  137.34
 2112.67  138.58 2142.52  137.57 2227.08  138.71 2286.78  137.44 2540.48  137.98
#Mann= 5 ,-1 , 0
       0      .1       0  329.96     .07       0 1083.01     .04       0
 1192.34     .07       0 1230.86     .15       0
#XS Ineff= 2 ,-1
       0 1039.91  136.32 1215.97 2540.48   136.6
Permanent Ineff=
       F       F
#Block Obstruct= 3 ,-1
  899.26  919.24     136 1237.13 1266.96  136.06 1371.36 1406.16  136.06
Bank Sta=1083.01,1192.34
XS Rating Curve= 0 ,0
Exp/Cntr=0.5,0.3

Type RM Length L Ch R = 1 ,16076.21,117.89,117.73,117.92
BEGIN DESCRIPTION:
Upstream Section - FRY ROAD
END DESCRIPTION:
XS GIS Cut Line= 6
3008075.8527955313885372.82883343007862.3079470213884910.9278544
3007739.4450037813884737.80287253007059.8046307713884070.1834729
3006740.4319099513883635.10068163006631.81828202 13883377.004413
#Sta/Elev= 30
       0  138.16   131.9  138.19  171.35  137.46  181.22  136.35   225.6   137.5
  285.07  136.23  543.67  136.18  647.35  137.18  810.15  136.38  913.69  137.41
  938.34  135.55  967.93  135.49  997.51  137.37 1124.99  137.72  1136.4  136.47
 1172.18  125.25 1196.22   125.2 1224.74  134.98 1235.63  136.69 1279.55  135.83
 1297.42  136.88 1311.68  136.29 1331.55  137.64 1430.94   135.6 1510.45  137.73
 1732.02  137.56 1940.57  136.73 2274.35  136.95 2484.33  136.76 2494.72  136.73
#Mann= 8 ,-1 , 0
       0     .07       0 1124.99     .04       0 1235.63     .07       0
 1279.55     .15       0 1732.02     .07       0 1940.57     .15       0
 2274.35     .07       0 2484.33     .15       0
#XS Ineff= 2 ,-1
       0  1177.1  136.32  1202.1 2494.72   136.6
Permanent Ineff=
       F       F
Bank Sta=1124.99,1235.63
XS Rating Curve= 0 ,0
Exp/Cntr=0.5,0.3

Type RM Length L Ch R = 2 ,16019   ,,,
BEGIN DESCRIPTION:
FRY ROAD
END DESCRIPTION:
Node Name=FRY ROAD
Bridge Culvert--1,0,-1,-1, 0
Deck Dist Width WeirC Skew NumUp NumDn MinLoCord MaxHiCord MaxSubmerge Is_Ogee
7.5,103,2.6,0, 60, 60, , , 0.98, 0, 0,0,,
       0   18.46   33.26   57.92  200.94  210.81   225.6  250.26  364.73  404.56
  429.45  439.41  449.37  568.36  637.47  652.29  681.91  750.99  780.57  795.36
  805.22  923.55  972.86  987.65 1061.47 1071.81 1071.92 1134.82 1193.62 1284.72
 1284.83 1321.42 1379.12 1391.19 1416.03 1445.85 1455.79 1490.57 1634.68 1644.62
 1654.56 1684.38 1694.32 1704.26 1724.15  1942.9 1957.75 1967.63 2007.16  2012.1
 2017.05 2026.93  2096.1  2180.1 2194.93 2204.81 2244.17 2273.65 2455.41 2494.72
  138.88  138.77  138.19  137.92  137.17  137.27  137.99  138.21  137.67  137.96
  137.82   137.5  137.79  137.16  137.31  137.05  137.35  137.35  137.07  136.67
  136.87   136.3  136.41  137.04  137.53  137.77  138.56  140.15  141.09  139.22
  137.72  137.19  137.42  136.83  136.62  136.64  137.09  137.48  137.84  137.65
  137.86   137.7  137.09  137.67  137.83  137.12   136.4  136.37  136.35  136.42
  136.83   136.9  136.89  137.55  137.48  137.05  137.78  137.88  136.92     137
                                                                                
                                                                                
                                                                                
                                                                                
                                                                                
                                                                                
       0   18.46   33.26   57.92  200.94  210.81   225.6  250.26  364.73  404.56
  429.45  439.41  449.37  568.36  637.47  652.29  681.91  750.99  780.57  795.36
  805.22  923.55  972.86  987.65 1061.47 1071.81 1071.92 1134.82 1193.62 1284.72
 1284.83 1321.42 1379.12 1391.19 1416.03 1445.85 1455.79 1490.57 1634.68 1644.62
 1654.56 1684.38 1694.32 1704.26 1724.15  1942.9 1957.75 1967.63 2007.16  2012.1
 2017.05 2026.93  2096.1  2180.1 2194.93 2204.81 2244.17 2273.65 2455.41 2494.72
  138.88  138.77  138.19  137.92  137.17  137.27  137.99  138.21  137.67  137.96
  137.82   137.5  137.79  137.16  137.31  137.05  137.35  137.35  137.07  136.67
  136.87   136.3  136.41  137.04  137.53  137.77  138.56  140.15  141.09  139.22
  137.72  137.19  137.42  136.83  136.62  136.64  137.09  137.48  137.84  137.65
  137.86   137.7  137.09  137.67  137.83  137.12   136.4  136.37  136.35  136.42
  136.83   136.9  136.89  137.55  137.48  137.05  137.78  137.88  136.92     137
                                                                                
                                                                                
                                                                                
                                                                                
                                                                                
                                                                                
BR Coef=-1 , 0 , 0 ,, 0 ,,,0.8,-1,,0,
WSPro=,,,, 1 ,,,, 0 ,,,, 0 ,,,,-1 ,-1 ,-1 , 0 , 0 , 0 , 0 , 0
Culvert=2,10,12,103,0.015,0.4,1,8,1,125.1,1183.1,124.47,1183.1,Culvert #1  , 0 ,7.5
Culvert Bottom n=0.015
Culvert=2,10,12,103,0.015,0.4,1,8,1,125.1,1196.1,124.47,1196.1,Culvert #2  , 0 ,10
Culvert Bottom n=0.015
BC Design=,, 0 ,, 0 ,,,,,,
BC Use User HTab Curves=0
BC User HTab FreeFlow(D)= 0

Type RM Length L Ch R = 1 ,15958.48,54.46,54.04,50.74
BEGIN DESCRIPTION:
Downstream Section - FRY ROAD
END DESCRIPTION:
XS GIS Cut Line= 6
3008156.6331457813885287.19252183007943.0882972813884825.2915427
3007820.2253540313884652.16656093007140.5849810213883984.5471612
3006821.2122601913883549.46436993006712.5986322813883291.3681014
#Sta/Elev= 30
       0  138.37  166.42  136.37  215.74  137.72  558.48  137.34  632.54  136.15
   667.1  136.82  731.26  136.11  790.43  137.43  893.97  136.94  928.48   135.5
  967.93  135.24  977.79  136.17  992.58  136.46 1115.22  137.61 1129.88  136.43
  1159.2  128.14 1186.33  124.79 1211.96  128.45 1240.39  136.76 1249.89  137.31
 1273.66  137.88 1306.92  137.03 1371.31  137.26 1406.09  135.35 1435.91  135.37
 1500.51   136.8 1719.18  137.37  1908.1  136.63  2371.9  137.14 2494.72  136.25
#Mann= 3 ,-1 , 0
       0     .07       0 1115.22     .04       0 1249.89     .07       0
#XS Ineff= 2 ,-1
       0  1177.1   135.8  1202.1 2494.72   135.8
Permanent Ineff=
       F       F
Bank Sta=1115.22,1249.89
XS Rating Curve= 0 ,0
Exp/Cntr=0.5,0.3

Type RM Length L Ch R = 1 ,15904.44,862.51,879.97,896.09
Node Name=P
XS GIS Cut Line= 6
3008253.0000790213885228.00005493008001.9999248513884748.0000306
3007839.9999207713884572.00005453007173.9999404413883934.0000182
3006980.0000003613883700.00015813006795.0000422713883328.9999159
#Sta/Elev= 30
       0  137.74   69.57     138  109.33  135.97  139.14   135.9  163.99     137
  228.59  137.47  432.34  136.79  546.65   137.8  765.92  136.24  870.67  137.46
  925.55  136.82  950.49  135.11  980.42  135.18 1065.23     138 1134.97  137.92
 1147.48  136.83 1150.21  134.87 1174.61  128.07 1201.71  124.71 1227.14  128.43
 1263.12  137.97  1376.7  137.35 1421.24  135.24 1450.94  135.12 1505.39  136.77
 1579.64  137.48 1882.77  136.45 1957.52  136.56 2037.31  138.09 2421.92  137.26
#Mann= 3 ,-1 , 0
       0     .07       0 1134.97     .04       0 1263.12     .07       0
#XS Ineff= 2 ,-1
       0 1071.48   135.8 1285.05 2421.92   135.8
Permanent Ineff=
       F       F
#Block Obstruct= 2 ,-1
   945.5  985.41  135.28 1416.29 1460.84  135.57
Bank Sta=1134.97,1263.12
XS Rating Curve= 0 ,0
Exp/Cntr=0.3,0.1

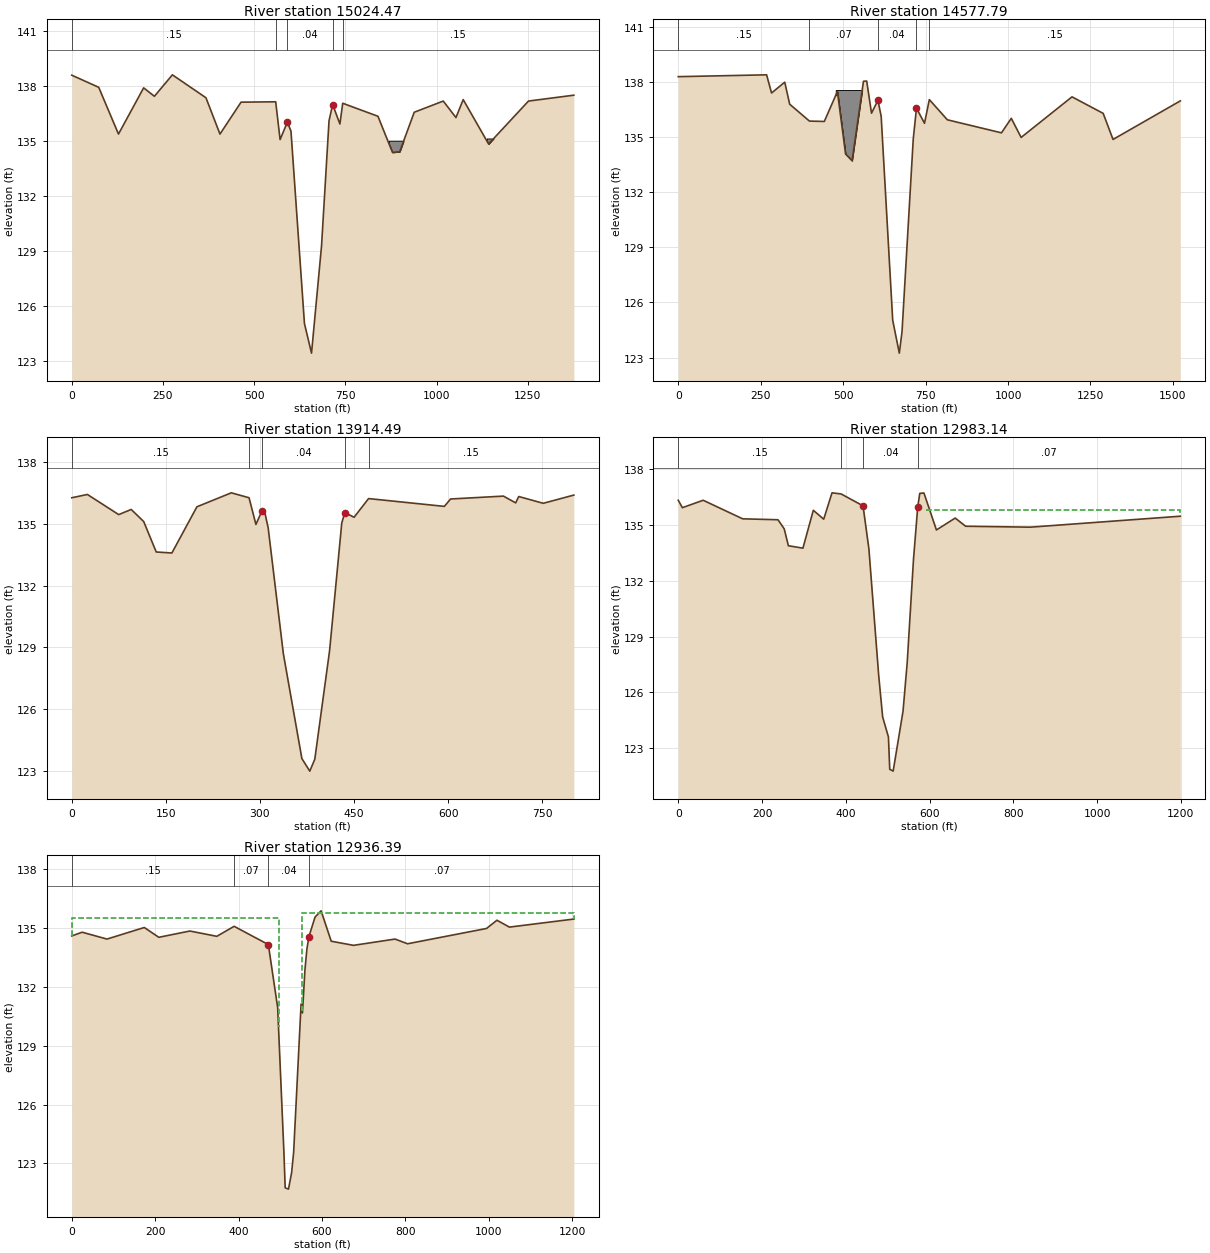
Type RM Length L Ch R = 1 ,15024.47,455.89,446.68,439.01
XS GIS Cut Line= 6
3008584.0000731913884320.99990043008394.0001251113884082.0000503
3008356.9998710313883982.99992023008184.99988694 13883656.999916
3008047.0001629413883480.99993993007853.9998927713883161.9999218
#Sta/Elev= 30
       0  138.58   73.87  137.92  128.04  135.37  196.98  137.89  226.53  137.43
  275.77   138.6  367.77  137.35  406.21  135.37     464  137.11  558.91  137.13
  571.01  135.07  590.88  136.02  600.81  135.53  637.75  125.04  657.13  123.43
  684.55  129.27  705.11   136.1  715.04  136.98  734.91  135.92  742.64  137.05
  839.24  136.34     879  134.37  898.88  134.41  938.64  136.56 1018.17  137.17
 1052.97  136.27 1072.85  137.25 1142.45  134.83 1251.81  137.17 1376.09  137.49
#Mann= 5 ,-1 , 0
       0     .15       0  558.91     .07       0  590.88     .04       0
  715.04     .07       0  742.64     .15       0
#Block Obstruct= 2 ,-1
  869.06  908.82  135.01 1137.48 1172.28  135.13
Bank Sta=590.88,715.04
XS Rating Curve= 0 ,0
Exp/Cntr=0.3,0.1

Type RM Length L Ch R = 1 ,14577.79,682.75,663.3,646.32
XS GIS Cut Line= 6
3008970.9999553613884086.00004233008831.9999052713883944.9999962
3008748.0000732813883699.0001601 3008686.9998672       13883615.
3008500.9999111113883381.00013993007878.9998427813883154.9999358
#Sta/Elev= 30
       0   138.3  267.98   138.4  282.98  137.41  322.97     138  337.97   136.8
  397.86  135.88  442.94  135.86  482.66  137.49  507.38  134.09  527.15  133.72
  561.75  138.05  571.49  138.06  586.09  136.31  605.56  137.01  615.38  136.14
  650.36  125.03  670.37  123.24  678.57   124.4  712.72  134.92  722.46  136.58
  746.82  135.76  761.45  137.05  816.12  135.95  980.09  135.24 1009.95  136.03
  1039.8  134.99 1194.06   137.2  1288.6   136.3 1318.45  134.88 1522.46  136.98
#Mann= 5 ,-1 , 0
       0     .15       0  397.86     .07       0  605.56     .04       0
  722.46     .07       0  761.45     .15       0
#Block Obstruct= 1 ,-1
  477.71  566.62  137.57
Bank Sta=605.56,722.46
XS Rating Curve= 0 ,0
Exp/Cntr=0.3,0.1

Type RM Length L Ch R = 1 ,13914.49,941.3,931.35,900.58
XS GIS Cut Line= 5
3009269.0000155313883161.99992183009052.0001214413883019.9998777
3008889.0001193613882931.0000557 3008657.999925213882872.9998436
3008541.0001591913882867.9998536
#Sta/Elev= 30
       0  136.28   24.94  136.44   74.81  135.46   94.76  135.71   114.7  135.12
  134.65  133.64  159.59  133.59  199.49  135.84  254.34  136.52  282.59  136.28
  293.54  134.98  303.32  135.65   308.2   135.5  313.09  134.81   337.3  128.68
  366.82  123.58  379.42  122.97   387.4  123.55  410.95  128.83  430.38  135.05
  435.27  135.56  450.01  135.33   473.1  136.24   593.9  135.86  603.83  136.22
   688.1  136.36  707.61  136.03  712.49  136.34  751.53  136.01  800.32  136.41
#Mann= 5 ,-1 , 0
       0     .15       0  282.59     .07       0  303.32     .04       0
  435.27     .07       0   473.1     .15       0
Bank Sta=303.32,435.27
XS Rating Curve= 0 ,0
Exp/Cntr=0.3,0.1

Type RM Length L Ch R = 1 ,12983.14,56.61,46.75,54.36
Node Name=O
XS GIS Cut Line= 6
3009812.9999117713882211.99985333009423.0000356113882138.0000013
3009379.0001236113882133.00001133009314.9999235313882119.0000393
3009260.0000335313882119.00003933008622.9999951913882122.0000333
#Sta/Elev= 30
       0  136.34    9.92  135.94   59.54  136.34  153.82  135.34  238.17  135.29
  253.06   134.8  262.98  133.89  297.72  133.76  322.53   135.8  347.34  135.32
  367.19  136.74   388.8  136.68  441.24  136.04  455.28  133.71  478.68  126.89
  488.04  124.67  501.88  123.59  504.98  121.85  513.14  121.75  536.75  124.98
  546.75  127.61  561.75  133.17  571.71  135.95  576.68  136.71  586.64  136.73
   616.5  134.74  661.29  135.38  686.17  134.94  840.45  134.89 1198.76  135.48
#Mann= 4 ,-1 , 0
       0     .15       0   388.8     .07       0  441.24     .04       0
  571.71     .07       0
#XS Ineff= 2 ,-1
       0  387.36   135.8  591.45 1198.76   135.8
Permanent Ineff=
       F       F
Bank Sta=441.24,571.71
XS Rating Curve= 0 ,0
Exp/Cntr=0.5,0.3

Type RM Length L Ch R = 1 ,12936.39,55.95,54.94,56.4
BEGIN DESCRIPTION:
Upstream Section - FREEMAN (FM 529)
END DESCRIPTION:
XS GIS Cut Line= 6
3009833.0208691113882091.65363733009450.5032614513882077.7347019
3009351.9703220313882073.92237353009283.89171803 13882070.896789
 3009157.660343213882067.40959133008629.4517539413882048.8486048
#Sta/Elev= 30
       0   134.6   24.86  134.79   84.51  134.44  173.99  135.03  208.78  134.53
  283.35  134.85  347.97  134.58  389.43  135.09  471.52  134.16  493.88  130.95
  508.92  123.55  511.93  121.76  519.85  121.69  527.33  122.53  532.18  123.56
  550.06  131.13  553.35  130.67  559.24  132.85  564.09  133.94  568.95  134.57
  583.52  135.56  598.09  135.88  622.38  134.33   675.8  134.12  775.53  134.44
  805.44   134.2  994.92  134.98 1019.85   135.4 1049.77  135.05 1204.34  135.46
#Mann= 4 ,-1 , 0
       0     .15       0  389.43     .07       0  471.52     .04       0
  568.95     .07       0
#XS Ineff= 2 ,-1
       0  495.89  135.49  552.68 1204.34  135.76
Permanent Ineff=
       F       F
Bank Sta=471.52,568.95
XS Rating Curve= 0 ,0
Exp/Cntr=0.5,0.3