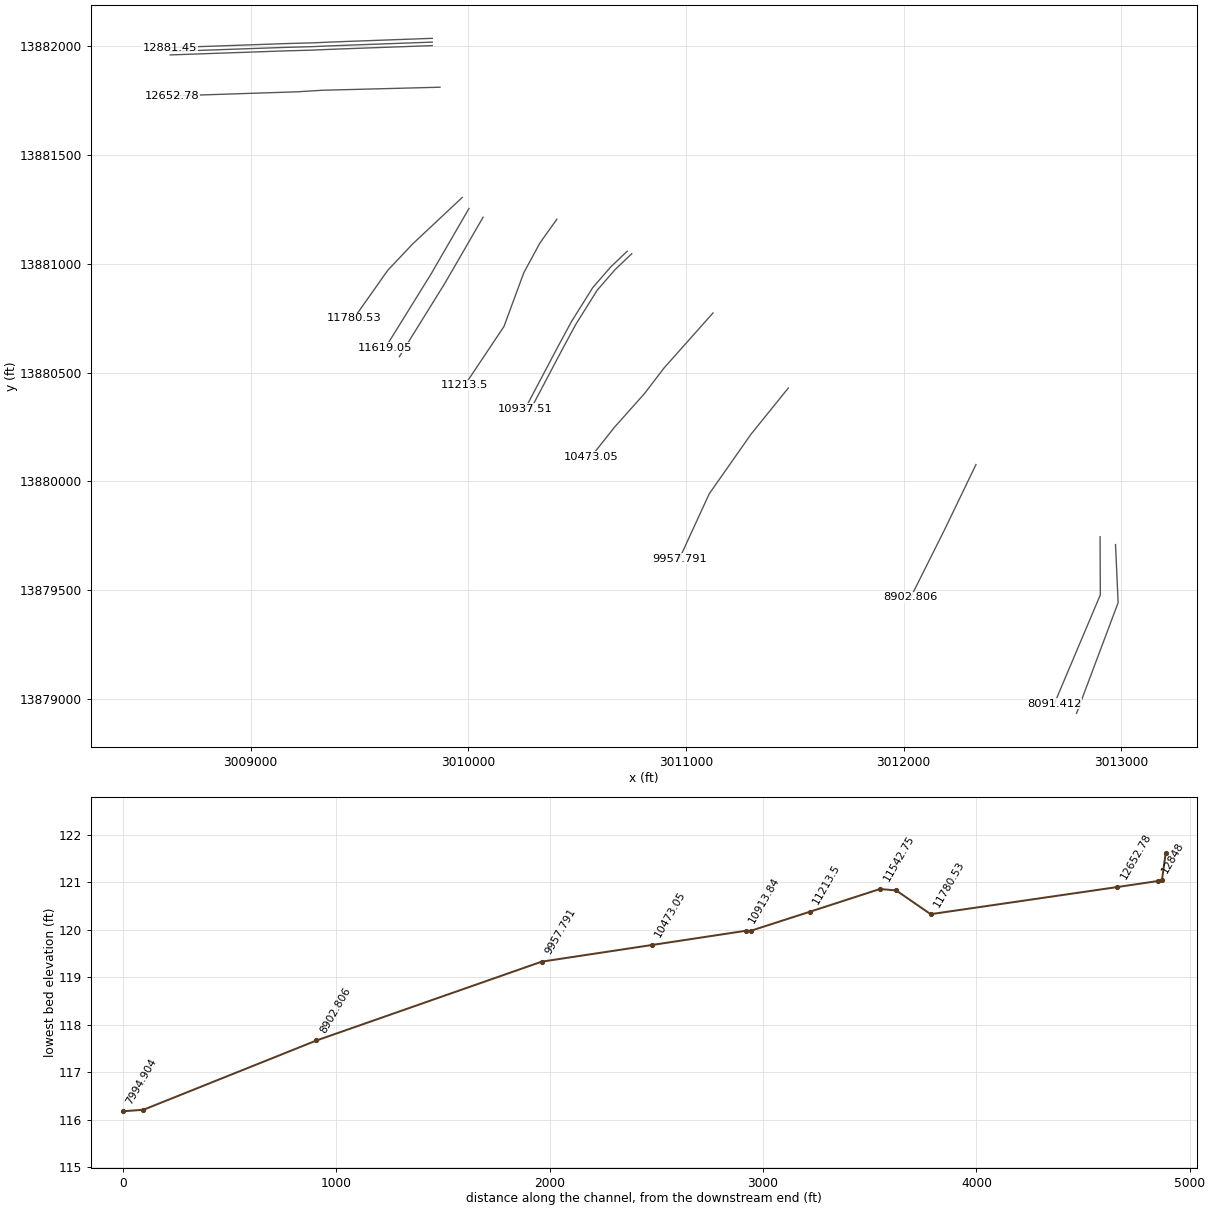
HEC-RAS study U120-00-00.prj: U120-00-00 2019 (Re-Study)

--- U120-00-00.g01 (geometry) --- (continued)

Type RM Length L Ch R = 3 ,12908.86,,,
BEGIN DESCRIPTION:
FREEMAN (FM 529)
END DESCRIPTION:
Node Name=FREEMAN (FM 529)
Bridge Culvert--1,0,-1,-1, 0
Deck Dist Width WeirC Skew NumUp NumDn MinLoCord MaxHiCord MaxSubmerge Is_Ogee
9,35,2.6,0, 197, 197, , , 0.98, 0, 0,0,,
       0    4.97    9.94   14.91   19.88   24.86   29.83    34.8   39.77   44.74
   49.71   54.68   59.65   64.62   69.59   74.57   79.54   84.51   89.48   94.45
   99.42  104.39  109.36  114.33  119.31  124.28  129.25  134.22  139.19  144.16
  149.13   154.1  159.07  164.04  169.02  173.99  178.96  183.93   188.9  193.87
  198.84  203.81  208.78  213.76  218.73   223.7  228.67  233.64  238.61  243.58
  248.55  253.52  258.49  263.47  268.44  273.41  278.38  283.35  288.32  293.29
  298.26  303.23  308.21  313.18  318.15  323.12  328.09  333.06  338.03     343
  347.97  352.94  357.92  362.89  367.86  372.83   377.8  382.77   387.7  392.63
  397.56  402.39  415.18  415.29   415.4  415.69  439.99  441.19  446.89  481.69
  495.49   495.6  495.69  495.79  495.89  510.89  513.89  513.99  521.89  529.29
  534.09  534.19  551.99  552.09  552.68  552.79  552.89  563.99  615.09  635.69
  678.59  704.69  742.79  770.59  772.78  772.89     773  795.59  800.99  824.29
  825.39  830.37  835.36  840.35  845.33  850.32  855.31  860.29  865.28  870.26
  875.25  880.24  885.22  890.21  895.19  900.18  905.17  910.15  915.14  920.13
  925.11   930.1  935.08  940.07  945.06  950.04  955.03  960.02     965  969.99
  974.97  979.96  984.95  989.93  994.92   999.9 1004.89 1009.88 1014.86 1019.85
 1024.84 1029.82 1034.81 1039.79 1044.78 1049.77 1054.75 1059.74 1064.72 1069.71
  1074.7 1079.68 1084.67 1089.66 1094.64 1099.63 1104.61  1109.6 1114.59 1119.57
 1124.56 1129.54 1134.53 1139.52  1144.5 1149.49 1154.48 1159.46 1164.45 1169.43
 1174.42 1179.41 1184.39 1189.38 1194.36 1199.35 1204.34
  135.55  135.56  135.63  135.64  135.61   135.6  135.64  135.65  135.66  135.66
  135.66  135.69  135.75  135.66  135.63  135.66  135.63  135.65  135.62  135.67
  135.67  135.57  135.53  135.57  135.58  135.52  135.55   135.5  135.49  135.55
  135.56  135.59  135.59  135.54  135.59  135.64  135.62  135.65  135.64  135.66
  135.65   135.6  135.63   135.6  135.55  135.63  135.65  135.68  135.68  135.69
  135.62  135.55  135.67  135.63  135.58  135.58  135.64  135.67  135.61   135.6
   135.6  135.65  135.56  135.61  135.55  135.73  135.72  135.78  135.73  135.66
  135.61  135.61  135.65   135.7  135.72  135.71  135.67  135.74  135.65  135.66
  135.68  136.59   136.5  138.16  138.16  138.16  138.14  138.14  138.13  138.06
  138.04  138.04  138.04  138.04  138.04  138.04  138.04  138.04  138.04  138.04
  138.04  138.04  138.04  138.04  138.04  138.04  138.04  138.07  138.18  138.19
   138.2   138.2   138.2   138.2   138.2   138.2   136.5  136.49  136.49  136.18
  135.76   135.8   135.8  135.79  135.81   135.8  135.82  135.84  135.79  135.81
  135.89   135.9  135.92  135.94  135.85  135.79  135.89  135.92  135.87  135.85
  135.84  135.91  135.95  135.91  135.92  135.95  135.96  135.97  135.97  136.01
  136.05  136.03  136.02  136.05  136.05  136.03  136.04  136.06  136.04  136.06
  136.05  136.03  136.06  136.13  136.07  136.03  136.12  136.13   136.1   136.1
  136.09  136.12  136.14  136.18  136.15  136.16  136.18  136.19   136.2   136.2
  136.23  136.24  136.29  136.31  136.29   136.2  136.25   136.3  136.32  136.34
  136.37  136.32  136.42  136.47  136.37  136.34  136.36
                                                                                
                                                                                
                                                                                
                                                                                
                                                                                
                                                                                
                                                                                
                                                                                
                                                                                
                                  134.81  134.81  134.81  134.81  134.81  134.81
  134.81  134.81  134.81  134.81  134.81
                                                                                
                                                                                
                                                                                
                                                                                
                                                                                
                                                                                
                                                                                
                                                                                
                                                        
       0    4.97    9.94   14.91   19.88   24.86   29.83    34.8   39.77   44.74
   49.71   54.68   59.65   64.62   69.59   74.57   79.54   84.51   89.48   94.45
   99.42  104.39  109.36  114.33  119.31  124.28  129.25  134.22  139.19  144.16
  149.13   154.1  159.07  164.04  169.02  173.99  178.96  183.93   188.9  193.87
  198.84  203.81  208.78  213.76  218.73   223.7  228.67  233.64  238.61  243.58
  248.55  253.52  258.49  263.47  268.44  273.41  278.38  283.35  288.32  293.29
  298.26  303.23  308.21  313.18  318.15  323.12  328.09  333.06  338.03     343
  347.97  352.94  357.92  362.89  367.86  372.83   377.8  382.77   387.7  392.63
  397.56  402.39  415.18  415.29   415.4  415.69  439.99  441.19  446.89  481.69
  495.49   495.6  495.69  495.79  495.89  510.89  513.89  513.99  521.89  529.29
  534.09  534.19  551.99  552.09  552.68  552.79  552.89  563.99  615.09  635.69
  678.59  704.69  742.79  770.59  772.78  772.89     773  795.59  800.99  824.29
  825.39  830.37  835.36  840.35  845.33  850.32  855.31  860.29  865.28  870.26
  875.25  880.24  885.22  890.21  895.19  900.18  905.17  910.15  915.14  920.13
  925.11   930.1  935.08  940.07  945.06  950.04  955.03  960.02     965  969.99
  974.97  979.96  984.95  989.93  994.92   999.9 1004.89 1009.88 1014.86 1019.85
 1024.84 1029.82 1034.81 1039.79 1044.78 1049.77 1054.75 1059.74 1064.72 1069.71
  1074.7 1079.68 1084.67 1089.66 1094.64 1099.63 1104.61  1109.6 1114.59 1119.57
 1124.56 1129.54 1134.53 1139.52  1144.5 1149.49 1154.48 1159.46 1164.45 1169.43
 1174.42 1179.41 1184.39 1189.38 1194.36 1199.35 1204.34
  135.55  135.56  135.63  135.64  135.61   135.6  135.64  135.65  135.66  135.66
  135.66  135.69  135.75  135.66  135.63  135.66  135.63  135.65  135.62  135.67
  135.67  135.57  135.53  135.57  135.58  135.52  135.55   135.5  135.49  135.55
  135.56  135.59  135.59  135.54  135.59  135.64  135.62  135.65  135.64  135.66
  135.65   135.6  135.63   135.6  135.55  135.63  135.65  135.68  135.68  135.69
  135.62  135.55  135.67  135.63  135.58  135.58  135.64  135.67  135.61   135.6
   135.6  135.65  135.56  135.61  135.55  135.73  135.72  135.78  135.73  135.66
  135.61  135.61  135.65   135.7  135.72  135.71  135.67  135.74  135.65  135.66
  135.68  136.59   136.5  138.16  138.16  138.16  138.14  138.14  138.13  138.06
  138.04  138.04  138.04  138.04  138.04  138.04  138.04  138.04  138.04  138.04
  138.04  138.04  138.04  138.04  138.04  138.04  138.04  138.07  138.18  138.19
   138.2   138.2   138.2   138.2   138.2   138.2   136.5  136.49  136.49  136.18
  135.76   135.8   135.8  135.79  135.81   135.8  135.82  135.84  135.79  135.81
  135.89   135.9  135.92  135.94  135.85  135.79  135.89  135.92  135.87  135.85
  135.84  135.91  135.95  135.91  135.92  135.95  135.96  135.97  135.97  136.01
  136.05  136.03  136.02  136.05  136.05  136.03  136.04  136.06  136.04  136.06
  136.05  136.03  136.06  136.13  136.07  136.03  136.12  136.13   136.1   136.1
  136.09  136.12  136.14  136.18  136.15  136.16  136.18  136.19   136.2   136.2
  136.23  136.24  136.29  136.31  136.29   136.2  136.25   136.3  136.32  136.34
  136.37  136.32  136.42  136.47  136.37  136.34  136.36
                                                                                
                                                                                
                                                                                
                                                                                
                                                                                
                                                                                
                                                                                
                                                                                
                                                                                
                          134.73  134.73  134.73  134.73  134.73  134.73  134.73
  134.73  134.73  134.73  134.73  134.73
                                                                                
                                                                                
                                                                                
                                                                                
                                                                                
                                                                                
                                                                                
                                                                                
                                                        
Pier Skew, UpSta & Num, DnSta & Num=  ,513.99, 2 ,513.99, 2 , 0 , 0 , 0 ,,
     1.4     1.4
  120.77  135.81
     1.4     1.4
  120.69  135.73
Pier Skew, UpSta & Num, DnSta & Num=  ,534.19, 2 ,534.19, 2 , 0 , 0 , 0 ,,
     1.4     1.4
  122.45  135.81
     1.4     1.4
  122.37  135.73
BR Coef=-1 , 1 , 1 ,0.9, 0 ,,,0.8,-1,1.2,0,
WSPro=,,,, 1 ,,,, 0 ,,,, 0 ,,,,-1 ,-1 ,-1 , 0 , 0 , 0 , 0 , 0
BC Design=,, 0 ,, 0 ,,,,,,
BC Use User HTab Curves=0
BC User HTab FreeFlow(D)= 0

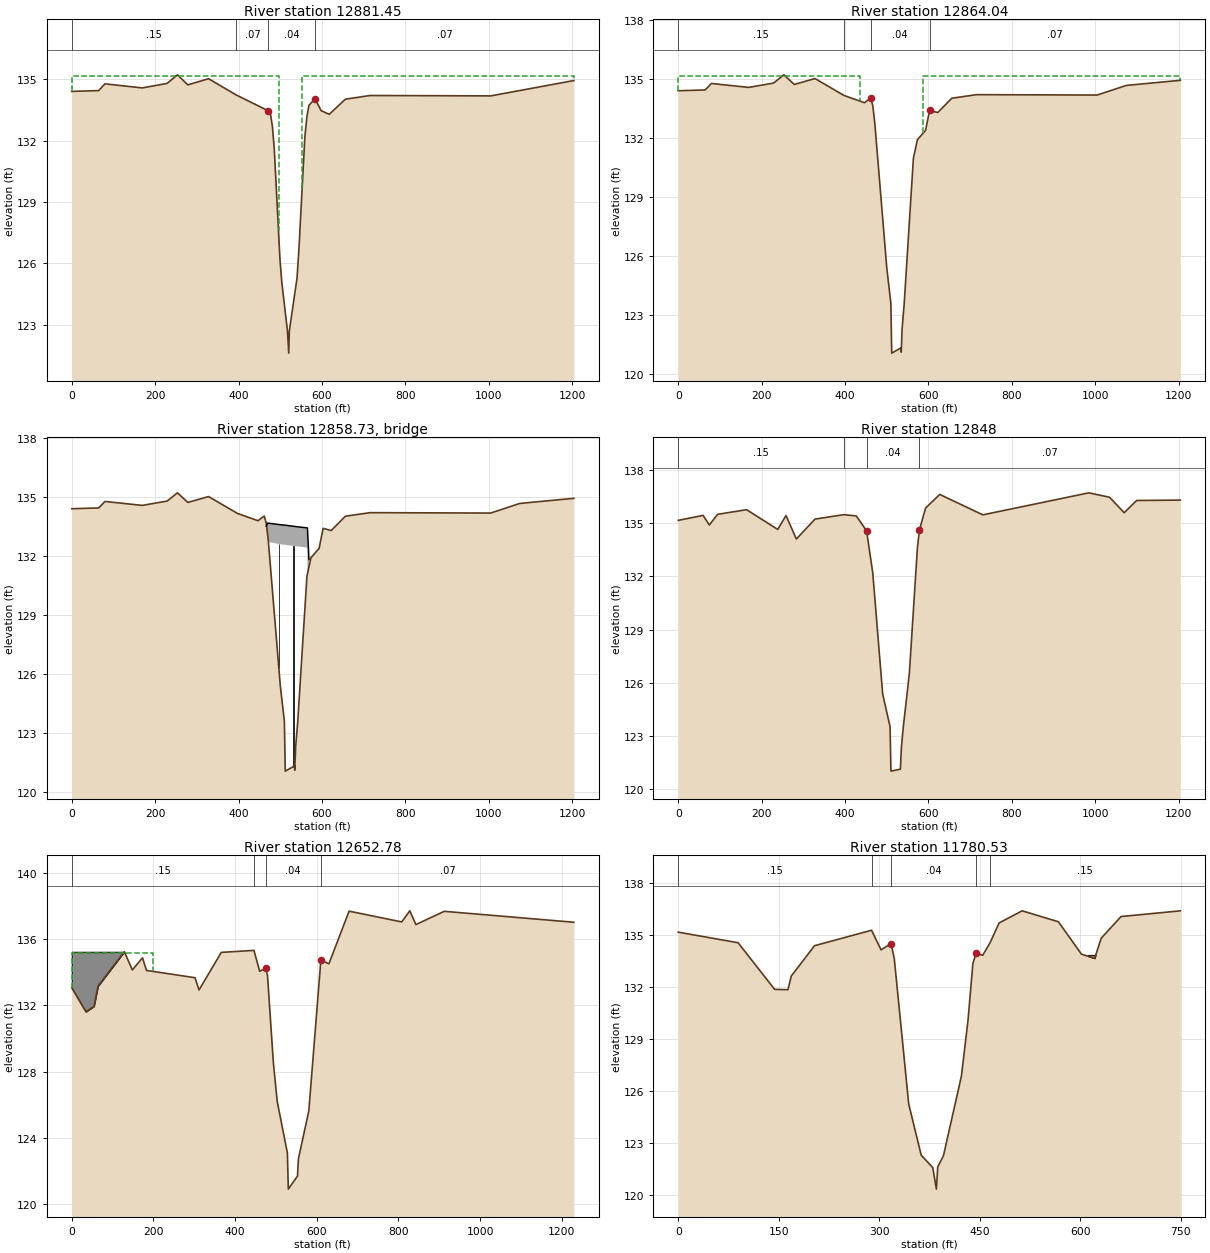
Type RM Length L Ch R = 1 ,12881.45,18.19,17.4,19.12
BEGIN DESCRIPTION:
Downstream Section - FREEMAN (FM 529)
END DESCRIPTION:
XS GIS Cut Line= 6
3009834.6035431213882036.76726413009452.0859354413882022.8483287
3009353.5529960213882019.03600043009285.4743920313882016.0104159
 3009159.243017213882012.52321813008631.0344279413881993.9622316
#Sta/Elev= 30
       0   134.4   64.62  134.44   79.54  134.77  169.02  134.57  228.67  134.79
  253.52  135.21  278.38  134.72  328.09  135.02  394.99  134.22  471.52  133.45
  476.45  133.33  481.38  132.67  485.86  131.55  499.29  126.24  503.77  125.07
   517.2  122.73   520.5  121.61  521.82  122.69  540.29  125.27  544.91   126.7
  559.24  132.21  564.09  133.17  568.95  133.72  583.52  134.04  598.09  133.46
  617.52  133.28  656.38  134.02  715.69   134.2 1004.89  134.18 1204.34  134.93
#Mann= 4 ,-1 , 0
       0     .15       0  394.99     .07       0  471.52     .04       0
  583.52     .07       0
#XS Ineff= 2 ,-1
       0  495.89  135.15  552.68 1204.34  135.15
Permanent Ineff=
       F       F
Bank Sta=471.52,583.52
XS Rating Curve= 0 ,0
Exp/Cntr=0.5,0.3

Type RM Length L Ch R = 1 ,12864.04,16.76,16.04,17.63
BEGIN DESCRIPTION:
Upstream Section - 12" PIPELINE
END DESCRIPTION:
XS GIS Cut Line= 6
3009834.4509843613882019.3637556 3009451.933376713882005.4448202
3009353.4004372813882001.63249193009285.3218332813881998.6069074
3009159.0904584413881995.1197096 3008630.881869213881976.5587231
#Sta/Elev= 30
       0   134.4   64.62  134.44   79.54  134.77  169.02  134.57  228.67  134.79
  253.52  135.21  278.38  134.72  328.09  135.02  397.56  134.16  446.87  133.79
  461.66  134.03  466.59  133.65  471.52  132.75  500.07  125.42  510.03  123.57
   512.1  121.04  534.62  121.31  534.84  121.09  537.06   122.3  541.84   123.5
  564.09  130.96  573.81  131.91  593.24  132.38  602.95   133.4  622.38  133.29
  656.38  134.02  715.69   134.2 1004.89  134.18  1074.7  134.67 1204.34  134.93
#Mann= 4 ,-1 , 0
       0     .15       0  397.56     .07       0  461.66     .04       0
  602.95     .07       0
#XS Ineff= 2 ,-1
       0  437.04  135.15     588 1204.34  135.15
Permanent Ineff=
       F       F
Bank Sta=461.66,602.95
XS Rating Curve= 0 ,0
Exp/Cntr=0.4,0.2

Type RM Length L Ch R = 3 ,12858.73,,,
BEGIN DESCRIPTION:
12" PIPELINE
END DESCRIPTION:
Node Name=12" PIPELINE
Bridge Culvert--1,0,-1,-1, 0
Deck Dist Width WeirC Skew NumUp NumDn MinLoCord MaxHiCord MaxSubmerge Is_Ogee
5,1,2.6,0, 14, 14, , , 0.98, 0, 0,0,,
  466.59  469.69  470.49   473.1  473.19  506.59  508.69  531.19  533.59  538.39
  562.48  562.59  565.29  568.95
  133.51  133.67  133.67  133.66  133.66  133.57  133.57  133.51   133.5  133.49
  133.43  133.43  133.42  131.81
          132.67  132.67  132.72   132.7  132.57  132.57  132.51   132.5  132.49
  132.43  132.41  132.42
  466.59  469.69  470.49   473.1  473.19  506.59  508.69  531.19  533.59  538.39
  562.48  562.59  565.29  568.95
  133.51  133.67  133.67  133.66  133.66  133.57  133.57  133.51   133.5  133.49
  133.43  133.43  133.42  131.81
          132.67  132.67  132.72   132.7  132.57  132.57  132.51   132.5  132.49
  132.43  132.41  132.42
Pier Skew, UpSta & Num, DnSta & Num=  ,496.59, 2 ,496.59, 2 , 0 , 0 , 0 ,,
     1.4     1.4
  125.12  133.61
     1.4     1.4
  125.12  133.61
Pier Skew, UpSta & Num, DnSta & Num=  ,531.39, 2 ,531.39, 2 , 0 , 0 , 0 ,,
     1.4     1.4
   120.3  133.51
     1.4     1.4
   120.3  133.51
BR Coef=-1 , 1 , 1 ,0.9, 0 ,,,0.8,-1,1.2,0,
WSPro=,,,, 1 ,,,, 0 ,,,, 0 ,,,,-1 ,-1 ,-1 , 0 , 0 , 0 , 0 , 0
BC Design=,, 0 ,, 0 ,,,,,,
BC Use User HTab Curves=0
BC User HTab FreeFlow(D)= 0

Type RM Length L Ch R = 1 ,12848   ,188.19,195.22,187.88
BEGIN DESCRIPTION:
Downstream Section - 12" PIPELINE
END DESCRIPTION:
Node Name=N
XS GIS Cut Line= 6
3009834.3099085213882003.32179293009451.7923008713881989.4028575
3009353.2593614513881985.59052923009285.1807574513881982.5649447
 3009158.949382613881979.07774693008630.7407933613881960.5167604
#Sta/Elev= 30
       0  135.15   59.65  135.43   74.57  134.89   94.45  135.49  164.04  135.75
  238.61  134.64  258.49  135.42  283.35   134.1  328.09  135.22  397.12  135.47
  427.14   135.4   451.8  134.56  466.59   132.2  490.33  125.38  508.14  123.53
  510.22  121.03  532.95  121.14  535.17  122.33  539.94  123.53  554.38  126.53
  573.81  133.63  578.66  134.61  593.24  135.84  627.23  136.61  730.65  135.46
  984.95   136.7 1034.81  136.45 1069.71  135.58 1099.63  136.27 1204.34  136.29
#Mann= 4 ,-1 , 0
       0     .15       0  397.12     .07       0   451.8     .04       0
  578.66     .07       0
#XS Ineff= 2 ,-1
       0  415.77  135.15   606.5 1204.34  135.15
Permanent Ineff=
       F       F
Bank Sta=451.8,578.66
XS Rating Curve= 0 ,0
Exp/Cntr=0.4,0.2

Type RM Length L Ch R = 1 ,12652.78,822.26,872.25,904.38
XS GIS Cut Line= 5
3009870.0001258613881811.99999713009405.0000716213881800.0000211
3009328.9998955313881798.00002513009216.0001215313881791.0000391
 3008640.999959213881772.0000771
#Sta/Elev= 30
       0  133.06   34.64  131.61   54.43  131.94   64.33  133.16  128.66  135.24
  148.45  134.14   173.2  134.87  183.09  134.11  301.86  133.67  311.75  132.93
  366.19   135.2  446.27  135.32  460.21  134.06  474.66  134.23  479.41  133.81
  493.66  128.57  503.17   126.2  528.11  123.08  530.39   120.9  552.92  121.69
  555.12  122.73  580.56  125.62   610.1  134.73  629.79  134.51   679.2  137.69
  808.15  137.04  827.98  137.71  842.86  136.88   912.3  137.68 1229.71  137.02
#Mann= 4 ,-1 , 0
       0     .15       0  446.27     .07       0  474.66     .04       0
   610.1     .07       0
#XS Ineff= 2 ,-1
       0  199.75  135.15  863.97 1229.71  135.15
Permanent Ineff=
       F       F
#Block Obstruct= 1 ,-1
       0  128.66  135.24
Bank Sta=474.66,610.1
XS Rating Curve= 0 ,0
Exp/Cntr=0.3,0.1

Type RM Length L Ch R = 1 ,11780.53,147.74,161.48,169.66
XS GIS Cut Line= 4
3009971.9999218613881305.00002693009744.0000497713881091.0001268
3009629.9999496913880970.00004073009473.9999336213880749.0001546
#Sta/Elev= 30
       0  135.15   89.34  134.54  143.94  131.85  163.79  131.83  168.76  132.62
   203.5  134.37  288.57  135.26  302.77  134.13  317.59  134.49  322.48  133.63
  344.03  125.24  362.68  122.29  379.95  121.57  385.38  120.33  387.34  121.61
  395.92  122.26  422.71  126.85  432.52  130.05  439.83  133.35  444.71  133.93
  454.49  133.82  465.39  134.53  478.94  135.68  513.37  136.38  567.47  135.75
   601.9  133.88  621.58  133.64  631.41   134.8  660.92  136.05  749.45  136.38
#Mann= 5 ,-1 , 0
       0     .15       0  288.57     .07       0  317.59     .04       0
  444.71     .07       0  465.39     .15       0
#Block Obstruct= 1 ,-1
  611.74  626.49  133.84
Bank Sta=317.59,444.71
XS Rating Curve= 0 ,0
Exp/Cntr=0.5,0.3

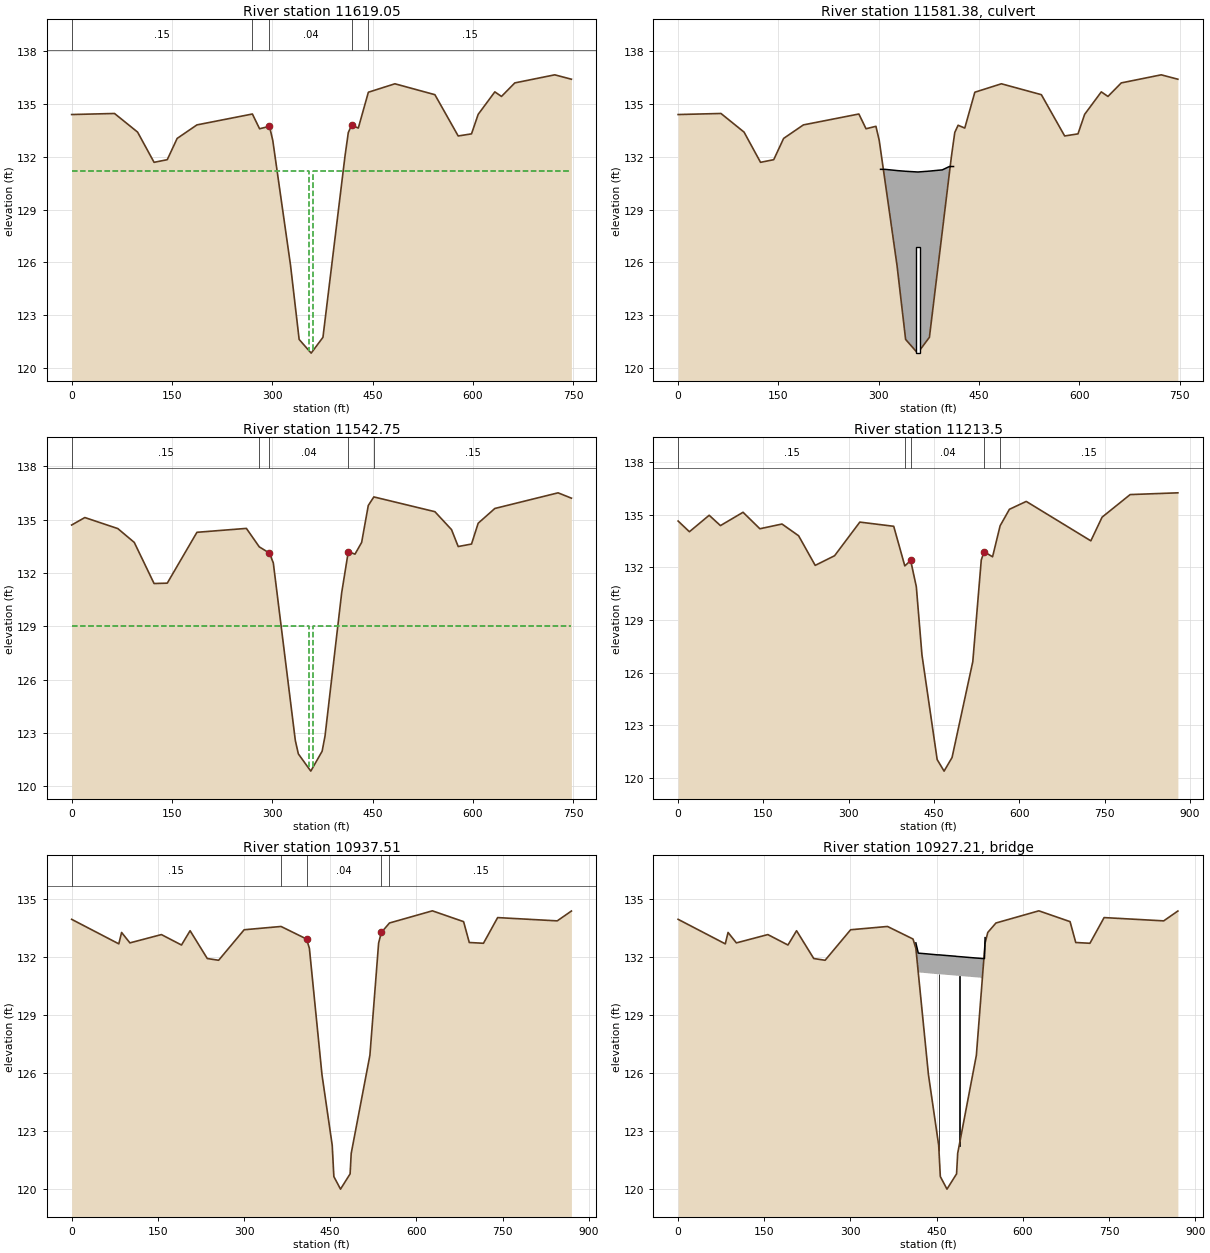
Type RM Length L Ch R = 1 ,11619.05,76.32,76.3,76.61
BEGIN DESCRIPTION:
Upstream Section - CONCRETE STRUCTURE
END DESCRIPTION:
Node Name=M
XS GIS Cut Line= 5
3010003.0598991113881254.34494443009840.1970358613880972.5754949
3009821.9556025313880941.17267053009812.5806212713880926.7780143
 3009618.507846713880613.4646645
#Sta/Elev= 30
       0  134.41    64.1  134.47   98.62  133.41  123.28  131.69     143  131.84
  157.79  133.05  187.38  133.82  270.34  134.44  281.07   133.6  295.86  133.74
   300.8  132.94  327.38  125.83  340.26  121.61  358.25  120.83  375.87  121.73
  408.83  132.04  413.81  133.39  418.79   133.8  428.75  133.64   443.8  135.68
  483.53  136.16   543.3  135.54  578.16  133.19  598.08  133.31  608.04  134.42
  632.95   135.7  642.91  135.44  662.83  136.21  722.59  136.67   747.5  136.42
#Mann= 5 ,-1 , 0
       0     .15       0  270.34     .07       0  295.86     .04       0
  418.79     .07       0   443.8     .15       0
#XS Ineff= 2 , 0
       0  355.25  131.18  361.25       0  131.19
Permanent Ineff=
       F       F
Bank Sta=295.86,418.79
XS Rating Curve= 0 ,0
Exp/Cntr=0.5,0.3

Type RM Length L Ch R = 2 ,11581.38,,,
BEGIN DESCRIPTION:
CONCRETE STRUCTURE
END DESCRIPTION:
Node Name=CONCRETE STRUCT
Bridge Culvert--1,0,-1,-1, 0
Deck Dist Width WeirC Skew NumUp NumDn MinLoCord MaxHiCord MaxSubmerge Is_Ogee
33,10,2.6,0, 12, 12, , , 0.98, 0, 1,1,,
  302.75  309.75  327.55  337.45  340.45  358.45  358.85  375.95  378.55  395.15
  405.65  411.95
  131.29  131.29  131.22  131.19  131.18  131.14  131.14  131.19   131.2  131.26
  131.45  131.45
                                                                                
                
  302.75  309.75  327.55  337.45  340.45  358.45  358.85  375.95  378.55  395.15
  405.65  411.95
  131.29  131.29  131.22  131.19  131.18  131.14  131.14  131.19   131.2  131.26
  131.45  131.45
                                                                                
                
BR Coef=-1 , 0 , 0 ,, 0 ,,,0.8,-1,,0,
WSPro=,,,, 1 ,,,, 0 ,,,, 0 ,,,,-1 ,-1 ,-1 , 0 , 0 , 0 , 0 , 0
Culvert=2,6,6,56,0.015,0.4,1,8,1,120.85,358.25,120.95,358.25,Culvert #1  , 0 ,7
Culvert Bottom n=0.015
BC Design=,, 0 ,, 0 ,,,,,,
BC Use User HTab Curves=0
BC User HTab FreeFlow(D)= 0

Type RM Length L Ch R = 1 ,11542.75,316.42,329.25,344.24
BEGIN DESCRIPTION:
Downstream Section - CONCRETE STRUCTURE
END DESCRIPTION:
Node Name=L
XS GIS Cut Line= 5
3010067.9459241913881214.22428983009905.0830609513880932.4548402
3009886.8416276113880901.05201593009877.4666463613880886.6573596
3009683.3938717813880573.3440098
#Sta/Elev= 30
       0   134.7   19.72  135.12   69.03   134.5   93.69  133.72  123.28  131.41
     143  131.43  187.38  134.29  261.35  134.51  280.66  133.47  295.86  133.12
  301.61  132.57  334.53  122.59  339.07  121.83  357.68  120.86  374.65  121.98
  378.95  122.83  403.85  130.88  413.81  133.21  423.77  133.06  433.73  133.72
  443.69   135.8  452.01  136.28   543.3  135.45   568.2  134.44  578.16  133.49
  598.08  133.63  608.04   134.8  632.95  135.63  727.57  136.51   747.5  136.21
#Mann= 5 ,-1 , 0
       0     .15       0  280.66     .07       0  295.86     .04       0
  413.81     .07       0  452.01     .15       0
#XS Ineff= 2 , 0
       0  355.25     129  361.25       0     129
Permanent Ineff=
       F       F
Bank Sta=295.86,413.81
XS Rating Curve= 0 ,0
Exp/Cntr=0.5,0.3

Type RM Length L Ch R = 1 ,11213.5 ,283.89,275.98,269.18
XS GIS Cut Line= 5
3010407.0000361113881204.99989883010328.9998640313881096.0001168
3010255.0000120313880959.00006273010163.9998659513880711.9999005
3009982.9998998613880441.0001144
#Sta/Elev= 30
       0  134.65   19.86  134.04   54.61  134.98   74.46  134.39  114.18  135.15
  143.77  134.21  182.69  134.48  211.89  133.81  241.08  132.12  275.14  132.67
  319.54  134.59  379.14  134.35  398.65  132.09  408.94   132.4  418.87  130.91
  428.81  127.01  455.55  121.04  467.71  120.38  481.75  121.16  518.21  126.63
  533.11  132.43  538.07   132.9  552.97  132.61  566.26  134.38   582.6  135.32
  612.22  135.77  725.79  133.52  745.54  134.87  794.92  136.16  878.86  136.26
#Mann= 5 ,-1 , 0
       0     .15       0  398.65     .07       0  408.94     .04       0
  538.07     .07       0  566.26     .15       0
Bank Sta=408.94,538.07
XS Rating Curve= 0 ,0
Exp/Cntr=0.4,0.2

Type RM Length L Ch R = 1 ,10937.51,23.71,23.67,23.76
BEGIN DESCRIPTION:
Upstream Section - 12" PIPELINE
END DESCRIPTION:
XS GIS Cut Line= 6
3010730.3225521913881058.15570433010653.4145695313880984.8530294
3010571.5948512713880890.4454098 3010474.669520213880735.6173074
3010415.0384058713880625.52303943010260.6794626113880332.8116825
#Sta/Elev= 30
       0  133.95    82.1  132.68   86.93  133.27  101.42  132.73  156.22  133.16
   191.2  132.62  206.19  133.36  236.11  131.92  255.86  131.83  300.29  133.41
  364.51  133.58   408.9  132.93  413.84  132.45  435.74  125.91  453.58  122.25
  456.44  120.63  468.02  119.98  484.71  120.77  486.63  121.83  519.17  126.91
  534.35  132.72  539.05  133.27  553.26  133.76  627.95  134.39  682.28  133.83
  692.16  132.75  716.85  132.71  741.55  134.04  845.27  133.87  869.96  134.38
#Mann= 5 ,-1 , 0
       0     .15       0  364.51     .07       0   408.9     .04       0
  539.05     .07       0  553.26     .15       0
#XS Ineff= 2 , 0
       0   408.9  132.93  539.05       0  133.27
Permanent Ineff=
       F       F
Bank Sta=408.9,539.05
XS Rating Curve= 0 ,0
Exp/Cntr=0.4,0.2

Type RM Length L Ch R = 3 ,10927.21,,,
BEGIN DESCRIPTION:
12" PIPELINE
END DESCRIPTION:
Node Name=12" PIPELINE
Bridge Culvert--1,0,-1,-1, 0
Deck Dist Width WeirC Skew NumUp NumDn MinLoCord MaxHiCord MaxSubmerge Is_Ogee
8,1,2.6,0, 17, 17, , , 0.98, 0, 0,0,,
  413.84  418.08  433.68  451.48  454.08  454.28  465.88  482.58  484.58  489.08
  516.98  526.08  526.57  526.68  529.08  533.28  534.35
  132.73   132.2  132.16  132.11  132.11  132.11  132.08  132.04  132.03  132.02
  131.95  131.93  131.93  131.93  131.92  131.92     133
   131.2   131.2  131.16  131.11  131.11  131.11  131.08  131.04  131.03  131.02
  130.95  130.93  130.93   130.9   130.9   130.9   130.9
  413.84  417.41  433.01  450.81  453.41  453.61  465.21  481.91  483.91  488.41
  516.31  525.41   525.9  526.01  528.41  532.61  534.35
  132.73   132.2  132.16  132.11  132.11  132.11  132.08  132.04  132.03  132.02
  131.95  131.93  131.93  131.93  131.92  131.92     133
   131.2   131.2  131.16  131.11  131.11  131.11  131.08  131.04  131.03  131.02
  130.95  130.93  130.93  130.93  130.93  130.93  130.93
Pier Skew, UpSta & Num, DnSta & Num=  ,454.12, 2 ,453.45, 2 , 0 , 0 , 0 ,,
     1.5     1.5
   119.6  132.11
     1.5     1.5
   119.6  132.11
Pier Skew, UpSta & Num, DnSta & Num=  ,489.12, 2 ,488.45, 2 , 0 , 0 , 0 ,,
     1.5     1.5
  121.06  132.02
     1.5     1.5
  121.06  132.02
BR Coef=-1 , 1 , 1 ,0.9, 0 ,,,0.8,-1,1.2,0,
WSPro=,,,, 1 ,,,, 0 ,,,, 0 ,,,,-1 ,-1 ,-1 , 0 , 0 , 0 , 0 , 0
BC Design=,, 0 ,, 0 ,,,,,,
BC Use User HTab Curves=0
BC User HTab FreeFlow(D)= 0

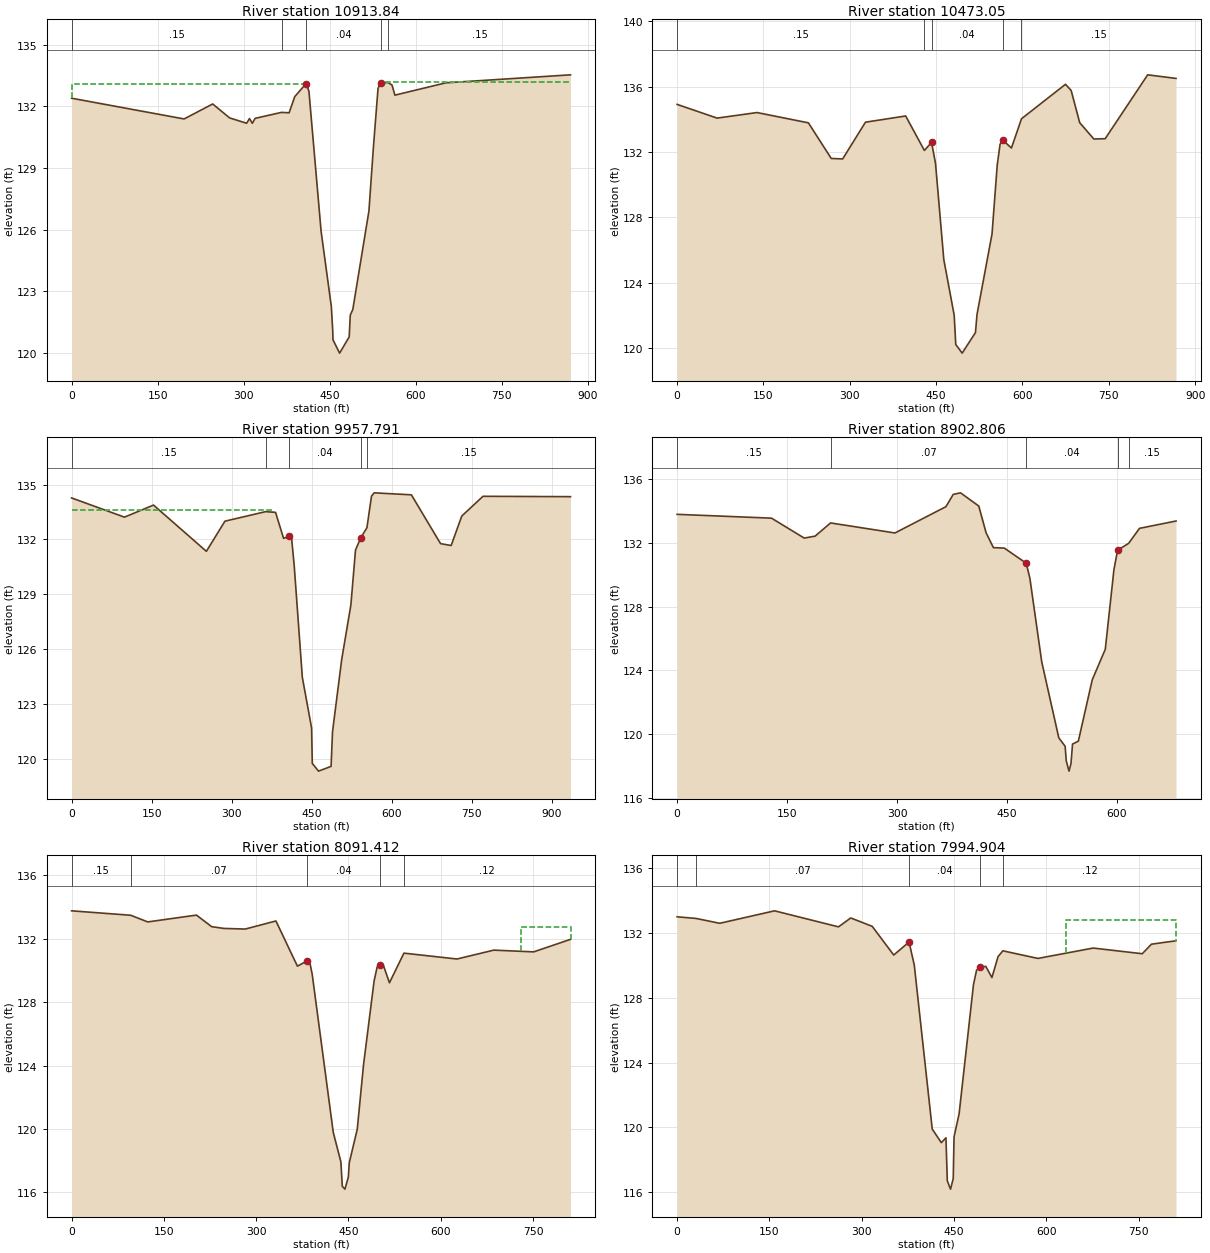
Type RM Length L Ch R = 1 ,10913.84,446.14,440.79,424.81
BEGIN DESCRIPTION:
Downstream Section - 12" PIPELINE
END DESCRIPTION:
Node Name=K
XS GIS Cut Line= 6
3010750.8828785313881046.42114773010673.9748958613880973.1184728
3010592.1551776113880878.71085323010495.2298465213880723.8827508
3010435.5987321913880613.78848283010281.2397889513880321.0771259
#Sta/Elev= 30
       0   132.4  196.19  131.39  245.99  132.12  275.61  131.44  305.23  131.18
  310.16  131.41   315.1  131.18  320.04  131.42  366.06  131.71  379.28  131.69
  389.15  132.48   408.9  133.11  413.84  132.74  435.07  125.91  452.91  122.25
  455.37  121.06  455.76  120.63  467.35  119.98  484.04  120.77  485.96  121.83
  490.37  122.11  518.49  126.91   526.1  129.95  534.35  132.88  539.05  133.16
  552.28  133.16   558.8  133.04  563.74  132.55  652.65  133.15  869.96  133.54
#Mann= 5 ,-1 , 0
       0     .15       0  366.06     .07       0   408.9     .04       0
  539.05     .07       0  552.28     .15       0
#XS Ineff= 2 , 0
       0   408.9  133.11  548.93       0  133.18
Permanent Ineff=
       F       F
Bank Sta=408.9,539.05
XS Rating Curve= 0 ,0
Exp/Cntr=0.4,0.2

Type RM Length L Ch R = 1 ,10473.05,512.27,515.26,521.02
XS GIS Cut Line= 6
3011123.9999144413880774.00010463010900.0000343613880521.9999524
3010808.9998882713880402.99986243010670.9998361913880247.9998443
3010564.0000501913880113.00011433010564.0000501913880113.0001143
#Sta/Elev= 30
       0  134.91   69.42  134.07  138.83  134.41  228.08  133.78  267.75   131.6
  287.58  131.57  327.25  133.82  397.09   134.2  429.56  132.09  442.03  132.58
  448.88  131.31  463.31  125.41  481.37     122   484.1  120.21  495.23  119.68
  518.34  120.94  520.98  122.04  547.12  126.98  556.15   131.2  561.09  132.47
  566.03  132.71  580.85  132.24   598.3  134.03  674.74  136.14  684.62  135.76
  699.42  133.79  724.03  132.79  743.72  132.81  817.55  136.72  866.76   136.5
#Mann= 5 ,-1 , 0
       0     .15       0  429.56     .07       0  442.03     .04       0
  566.03     .07       0   598.3     .15       0
#XS Ineff= 2 , 0
       0  397.09   134.2  674.74       0   134.2
Permanent Ineff=
       F       F
Bank Sta=442.03,566.03
XS Rating Curve= 0 ,0
Exp/Cntr=0.3,0.1

Type RM Length L Ch R = 1 ,9957.791,1013.8,1054.99,1031.31
XS GIS Cut Line= 4
3011469.9998786213880429.00013843011298.9998925313880216.9999063
3011106.9999484413879943.00012623010969.99989437 13879645.000066
#Sta/Elev= 30
       0  134.27   99.04  133.22  153.52  133.88  252.56  131.35  287.35     133
  363.52  133.52  382.23  133.48  397.21  132.06   407.2  132.17  412.19  132.09
  417.19  130.56  432.38  124.46  449.73  121.69  451.07  119.75  462.76  119.33
  486.25  119.59  488.94  121.48  506.08  125.42  523.37  128.42  532.04  131.42
  542.03   132.1  553.42  132.64     562  134.37  566.99  134.55  636.76  134.44
  691.42  131.77   711.3  131.67  731.18  133.28  770.94  134.36  934.93  134.34
#Mann= 5 ,-1 , 0
       0     .15       0  363.52     .07       0   407.2     .04       0
  542.03     .07       0  553.42     .15       0
#XS Ineff= 2 , 0
       0  377.24  133.63  566.99       0  133.63
Permanent Ineff=
       F       F
Bank Sta=407.2,542.03
XS Rating Curve= 0 ,0
Exp/Cntr=0.3,0.1

Type RM Length L Ch R = 1 ,8902.806,786.11,811.39,795.08
XS GIS Cut Line= 3
3012332.0001231113880076.99985823012188.0000830313879778.0001281
3012032.0000669513879466.0000959
#Sta/Elev= 30
       0  133.79  128.78  133.55  173.36   132.3  188.22  132.42   209.4  133.25
   297.2  132.62  366.75  134.27  376.72  135.04  386.68  135.14   411.6  134.31
  421.57  132.63  431.53   131.7  446.48  131.67  476.38  130.72  481.37  129.76
  497.48  124.53  520.77  119.76  529.41  119.23  530.96  118.31  534.69  117.67
  537.39  118.14   539.5  119.37  547.42  119.55   566.4   123.4  584.19  125.32
  595.98  130.31  600.96  131.53  616.09  131.97  630.86  132.91   680.7  133.37
#Mann= 5 ,-1 , 0
       0     .15       0   209.4     .07       0  476.38     .04       0
  600.96     .07       0  616.09     .15       0
Bank Sta=476.38,600.96
XS Rating Curve= 0 ,0
Exp/Cntr=0.3,0.1

Type RM Length L Ch R = 1 ,8091.412,94.16,96.51,97.59
XS GIS Cut Line= 3
3012902.0826443613879745.09632253012903.2404504413879477.8294686
3012691.74677895 13878976.997465
#Sta/Elev= 30
       0  133.77   96.05  133.49  123.74  133.07  202.93   133.5  227.67  132.77
  247.47  132.66  282.23  132.62  332.11  133.13  367.02  130.28  381.99  130.59
  386.97  130.55  390.98  129.79  425.26   119.8  437.68  117.93  440.01  116.39
  444.23  116.21  449.77  116.96  451.32  117.87   464.3  119.99  474.49  124.05
  491.71  129.35   496.7  130.23  501.69  130.37  506.68  130.34  516.65  129.23
  540.15   131.1  626.38  130.73  686.23  131.29  751.07  131.18  810.92  131.97
#Mann= 5 ,-1 , 0
       0     .15       0   96.05     .07       0  381.99     .04       0
  501.69     .07       0  540.15     .12       0
#XS Ineff= 2 ,-1
       0  212.63  132.69  731.01  810.92  132.78
Permanent Ineff=
       F       F
Bank Sta=381.99,501.69
XS Rating Curve= 0 ,0
Exp/Cntr=0.3,0.1

Type RM Length L Ch R = 1 ,7994.904,89.97,111.6,126.84
Node Name=J
XS GIS Cut Line= 3
3012973.00015344 13879708.9999383012985.0001294513879442.0001439
3012793.9998552813878932.9998496
#Sta/Elev= 30
       0     133    30.7   132.9   69.29   132.6  158.38  133.37  262.32  132.38
  282.23  132.93  317.15  132.41  352.06  130.64     377  131.44  385.49  130.02
  414.67  119.89  429.47  119.05  436.95  119.35  439.17  116.69  444.41  116.18
   448.8  116.83  450.11  119.41  458.34  120.83  481.74  128.82  486.73   129.7
  491.71  129.88  501.69  129.94  511.67  129.25  521.64  130.54  529.43   130.9
  586.48  130.43  676.26  131.07  756.06  130.72  771.02  131.31  810.92  131.52
#Mann= 5 ,-1 , 0
       0     .15       0    30.7     .07       0     377     .04       0
  491.71     .07       0  529.43     .12       0
#XS Ineff= 2 ,-1
       0  295.57  132.69  631.34  810.92  132.78
Permanent Ineff=
       F       F
Bank Sta=377,491.71
XS Rating Curve= 0 ,0
Exp/Cntr=0.5,0.3