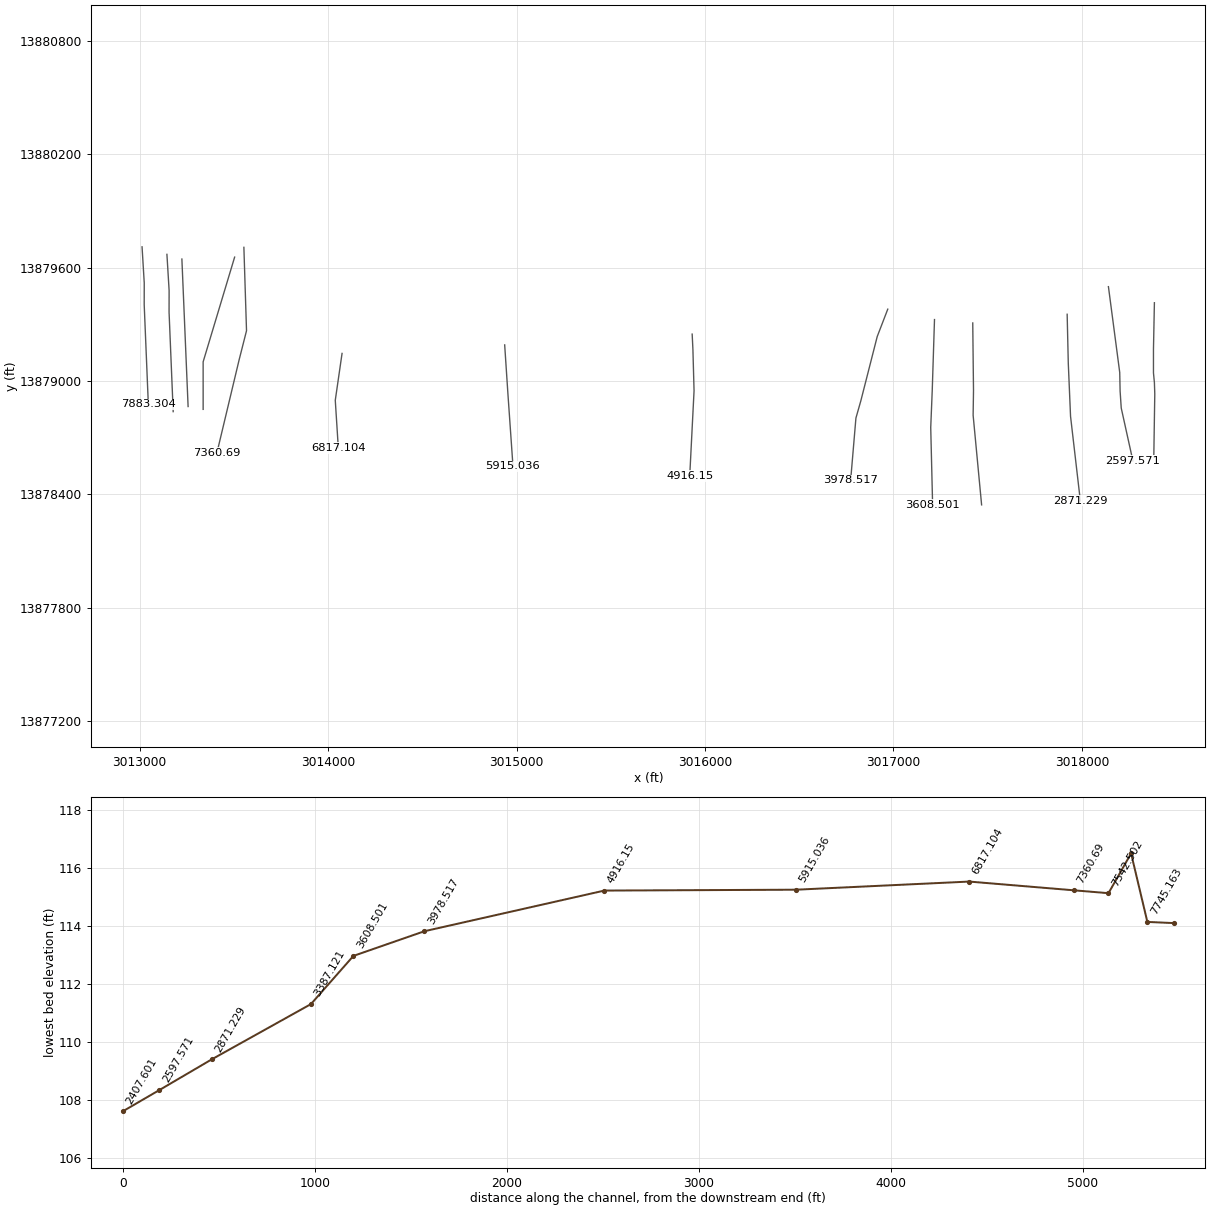
HEC-RAS study U120-00-00.prj: U120-00-00 2019 (Re-Study)

--- U120-00-00.g01 (geometry) --- (continued)

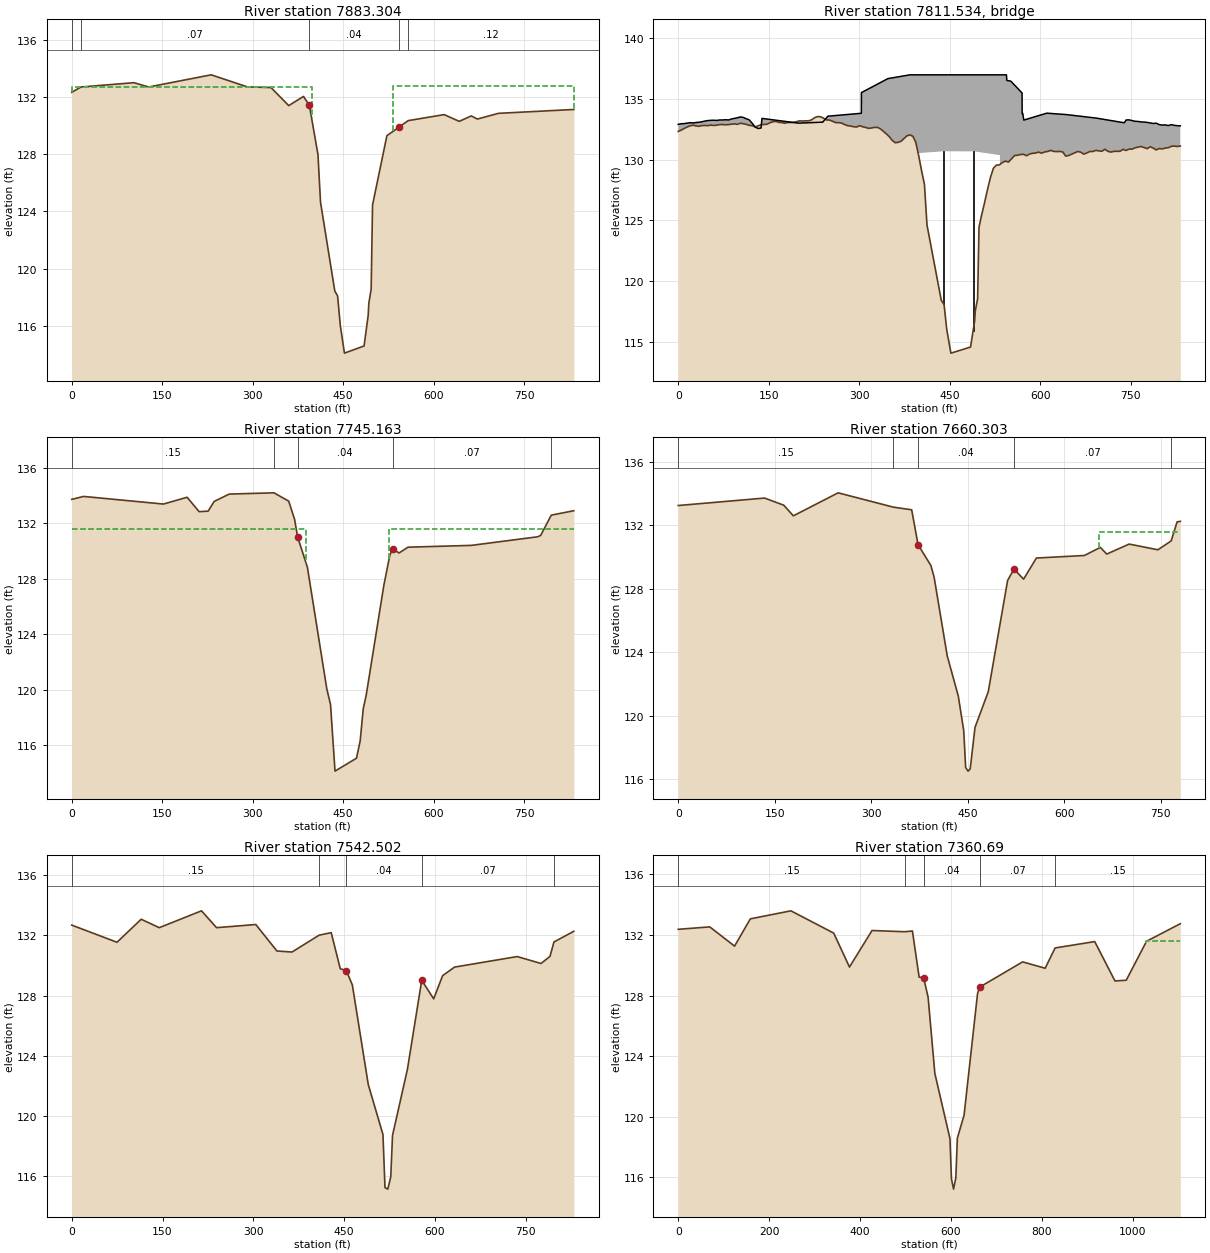
Type RM Length L Ch R = 1 ,7883.304,134.45,138.14,145.03
BEGIN DESCRIPTION:
Upstream Section - GREENHOUSE RD
U20_200
END DESCRIPTION:
XS GIS Cut Line= 5
3013012.6040768613879709.55997633013024.2457858613879518.6335209
3013023.9829911113879403.97167673013030.2871123613879252.4660742
3013045.8766481113878877.8178734
#Sta/Elev= 30
       0  132.32    15.3  132.69     103  132.99  127.52  132.69  231.16  133.54
  290.99   132.7   330.4  132.65  359.75  131.39  384.21  132.03  393.99  131.41
  408.25  127.97  412.51  124.63  436.17  118.44  440.82  118.09  445.33  116.02
  452.15   114.1  484.71   114.6  491.48  116.72   492.6  117.58  496.46  118.57
  498.76  124.45  522.58  129.29  542.57  129.88  557.75  130.34  617.57  130.76
  642.57  130.29  662.56  130.67  672.56  130.45  707.56  130.85  832.55  131.12
#Mann= 5 ,-1 , 0
       0     .15       0    15.3     .07       0  393.99     .04       0
  542.57     .07       0  557.75     .12       0
#XS Ineff= 2 ,-1
       0   397.8  132.69  533.41  832.55  132.78
Permanent Ineff=
       F       F
Bank Sta=393.99,542.57
XS Rating Curve= 0 ,0
Exp/Cntr=0.5,0.3

Type RM Length L Ch R = 3 ,7811.534,,,
BEGIN DESCRIPTION:
GREENHOUSE RD
U20_200
END DESCRIPTION:
Node Name=GREENHOUSE RD
Bridge Culvert--1,0,-1,-1, 0
Deck Dist Width WeirC Skew NumUp NumDn MinLoCord MaxHiCord MaxSubmerge Is_Ogee
20,102,2.6,0, 73, 71, , , 0.98, 0, 0,0,,
       0     4.9    9.81   14.71   19.62   24.52   29.43   34.33   39.24   44.14
   49.05   53.95   58.86   63.76   68.66   73.57   78.47   83.38   88.28   93.19
   98.09     103   107.9  112.81  117.71  122.62  127.52  132.43  137.33 138.874
 199.207 239.578  248.15 303.668  303.77 347.731 384.239 395.194 395.858 440.927
 490.791 533.211 533.413 544.229 544.854 551.517 570.127 570.329 571.247 572.983
  611.16 644.163 692.327 739.746  742.56  747.56  752.56  757.56  762.56  767.56
  772.56  777.56  782.56  787.56  792.56  797.56  802.55  807.55  812.55  817.55
  822.55  827.55  832.55
   132.9  132.95  132.96     133  133.04  133.01  133.05  133.07  133.11  133.17
  133.21  133.23  133.24  133.22  133.26  133.26  133.28  133.26  133.34  133.39
  133.44  133.51  133.47  133.36  133.27  132.99  132.68  132.56   132.6  133.39
     133  133.08  133.57  133.81  135.51  136.66  136.97  136.97  136.97  136.97
  136.97  136.97  136.97  136.97  136.51  136.45  135.48  133.77  133.81  133.25
  133.82   133.7  133.42  133.03  133.26  133.27  133.21  133.15  133.14   133.1
  133.09  133.06  133.02  132.97     133  132.88  132.84  132.86   132.8  132.88
  132.82  132.79  132.78
                                                                                
                                                                                
                                                                                
                                                          130.42  130.53  130.69
  130.68  130.37  130.49
                                                                                
                                                                                
                        
       0     4.9    9.81   14.71   19.62   24.52   29.43   34.33   39.24   44.14
   49.05   53.95   58.86   63.76   68.66   73.57   78.47   83.38   88.28   93.19
   98.09     103   107.9  112.81  117.71  122.62  127.52  132.43 133.439 232.238
  240.81 252.713  280.74  305.37 306.362 355.589  388.58 388.593 433.686 483.733
 525.608 526.184 536.645  536.65 553.415 599.828 599.947 636.823 684.987 732.406
  732.56  737.56  742.56  747.56  752.56  757.56  762.56  767.56  772.56  777.56
  782.56  787.56  792.56  797.56  802.55  807.55  812.55  817.55  822.55  827.55
  832.55
   132.9  132.95  132.96     133  133.04  133.01  133.05  133.07  133.11  133.17
  133.21  133.23  133.24  133.22  133.26  133.26  133.28  133.26  133.34  133.39
  133.44  133.51  133.47  133.36  133.27  132.99  132.68  132.56  133.39  133.08
  133.57   133.7  133.85  133.85  134.83  136.98  136.97  136.96  136.95  136.94
  136.93  136.92  136.92  136.44  136.44  135.21  133.49   133.7  133.42  133.03
  133.32  133.28  133.26  133.27  133.21  133.15  133.14   133.1  133.09  133.06
  133.02  132.97     133  132.88  132.84  132.86   132.8  132.88  132.82  132.79
  132.78
                                                                                
                                                                                
                                                                                
                                                  130.87  130.69  130.69  130.61
   130.5 130.741
                                                                                
                                                                                
        
Pier Skew, UpSta & Num, DnSta & Num=  ,440, 2 ,440, 2 , 0 , 0 , 0 ,,
    1.35    1.35
     110     131
    1.35    1.35
     110     131
Pier Skew, UpSta & Num, DnSta & Num=  ,489, 2 ,489, 2 , 0 , 0 , 0 ,,
    1.35    1.35
     110     131
    1.35    1.35
     110     131
Abutment Skew #Up #Dn= , 2 , 3
  387.85  433.13
  130.42  116.55
  388.48  388.58     434
  130.87  130.87  116.17
Abutment Skew #Up #Dn= , 3 , 4
  488.27  533.41  533.43
   116.1  130.49  130.49
  480.73  525.87  526.18  526.19
  116.29 130.741 130.741 130.741
BR Coef=-1 , 1 , 1 ,0.9, 0 ,,,0.8,-1,1.2,0,
WSPro=,,,, 1 ,,,, 0 ,,,, 0 ,,,,-1 ,-1 ,-1 , 0 , 0 , 0 , 0 , 0
BR U #Sta/Elev= 164
       0  132.32     4.9  132.42    9.81  132.56   14.71  132.68    15.3  132.69
   19.62  132.78   24.52  132.83   29.43  132.77   34.33  132.74   39.24   132.8
   44.14  132.81   49.05  132.79   53.95  132.84   58.86  132.81   63.76  132.83
   68.66  132.88   73.57  132.88   78.47  132.86   83.38  132.88   88.28  132.91
   93.19  132.94   98.09   132.9     103  132.99   107.9  132.95  112.81   132.9
  117.71  132.82  122.62  132.79  127.52  132.69  132.43  132.78  137.33  132.87
  142.23  132.89  147.14  132.91  152.04  133.03  156.95  133.11  161.85  133.14
  166.76  133.06  171.66  133.05  176.57  132.99  181.47  133.05  186.38  133.05
  191.28  133.07  196.27  133.12  201.25  133.19  206.24  133.17  211.22  133.19
  216.21  133.19  221.19  133.27  226.18  133.45  231.16  133.54  236.15  133.52
  241.13   133.4  246.12  133.26   251.1  133.25  256.09  133.15  261.08  133.04
  266.06  133.04  271.05     133  276.03  132.88  281.02  132.79     286  132.76
  290.99   132.7  295.97  132.68  300.96  132.79  305.94   132.7  310.83  132.64
  315.73  132.57  320.62   132.6  325.51  132.65   330.4  132.65  335.29  132.53
  340.18  132.33  345.08  132.12  349.97  131.89  354.86  131.58  359.75  131.39
  364.64  131.42  369.53  131.51  374.42  131.73  379.32  131.96  384.21  132.03
   389.1  131.92  393.99  131.41  398.88  130.29  403.77  129.03  408.25  127.97
  412.51  124.63  436.17  118.44  440.82  118.09  445.33  116.02  452.15   114.1
  457.58  114.18  484.71   114.6  491.48  116.72   492.6  117.58  496.46  118.57
  498.76  124.45  502.58  125.34  507.58  126.38  512.58  127.48  517.58  128.51
  522.58  129.29  527.57  129.55  532.57  129.57  537.57  129.76  542.57  129.88
  547.57   129.8  552.57  130.06  557.57  130.34  557.75  130.34  562.57  130.36
  567.57  130.42  572.57  130.44  577.57  130.32  582.57  130.46  587.57  130.52
  592.57  130.54  597.57  130.62  602.57  130.53  607.57  130.63  612.57  130.67
  617.57  130.76  622.57  130.68  627.57  130.66  632.57  130.68  637.57  130.63
  642.57  130.29  647.57  130.34  652.57  130.45  657.57  130.56  662.56  130.67
  667.56  130.61  672.56  130.45  677.56  130.55  682.56  130.67  687.56  130.67
  692.56  130.76  697.56  130.72  702.56  130.69  707.56  130.85  712.56  130.68
  717.56  130.62  722.56  130.68  727.56  130.69  732.56  130.68  737.56  130.85
  742.56  130.75  747.56  130.87  752.56  130.86  757.56  130.97  762.56  131.03
  767.56  131.08  772.56  130.99  777.56   130.9  782.56  131.06  787.56  130.95
  792.56   130.8  797.56  130.91  802.55  130.88  807.55  130.95  812.55  130.98
  817.55  131.09  822.55  131.12  827.55  131.08  832.55  131.12
BR U #Mann= 9
       0     .15    15.3     .07  384.21     .04  393.99    .015  452.15     .04
  484.71    .015  532.57     .04  542.57     .07  557.75     .12
BR D #Sta/Elev= 159
       0  133.74     4.9  133.75    9.81  133.82   14.71   133.9   19.62  133.95
   24.52   133.9   29.43  133.83   34.33   133.8   39.24  133.75   44.14  133.73
   49.05  133.65   53.95  133.61   58.86  133.56   63.76  133.54   68.66  133.56
   73.57  133.56   78.47  133.56   83.38  133.66   88.28  133.63   93.19  133.67
   98.09  133.64     103  133.67   107.9  133.58  112.81   133.5  117.71   133.5
  122.62  133.53  127.52  133.59  132.43  133.55  137.33  133.54  142.23  133.48
  147.14  133.43  152.04   133.4  156.95  133.43  161.85  133.41  166.76  133.44
  171.66   133.5  176.57  133.55  181.47  133.61  186.38  133.74  191.28  133.89
  196.27  133.71  201.25  133.37  206.24  132.97  211.22  132.85  216.21  132.88
  221.19  132.91  226.18  132.89  231.16  133.33  236.15  133.59  241.13  133.75
  246.12  133.83   251.1  133.93  256.09  134.06  261.08  134.12  266.06  134.11
  271.05  134.11  276.03  134.09  281.02  134.13     286  134.16  290.99  134.18
  295.97   134.1  300.96  134.06  305.94  134.03  310.83  134.07  315.73  134.11
  320.62  134.16  325.51  134.18   330.4  134.19  333.24   134.2  335.29  134.21
  340.18  134.18  345.08  134.13  349.97  134.04  354.86  133.89  359.75  133.61
  364.64  133.14  369.53  132.29  374.42  131.04  379.32  130.21  384.21   129.8
   389.1  129.18  390.75  128.84  415.32  122.18  422.92  120.07  429.08  118.95
  431.71  117.31  436.51  114.14  457.58  114.69  472.12  115.07  478.29  116.33
  483.32  118.63  488.29  119.63  510.89  125.64  512.58  126.12  517.58  127.56
  522.58  128.77  527.57  129.74  532.57  130.17  537.57   130.1  542.57  129.87
  547.57  130.09  552.57  130.18  557.57  130.29  562.57  130.18  567.57  130.16
  572.57  130.21  577.57  130.16  582.57   130.2  587.57  130.28  592.57  130.33
  597.57  130.41  602.57  130.45  607.57  130.42  612.57  130.47  617.57  130.54
  622.57  130.58  627.57  130.55  632.57  130.56  637.57  130.58  642.57  130.51
  647.57  130.57  652.57  130.48  657.57  130.62  662.56  130.42  667.56  130.57
  672.56  130.59  677.56  130.64  682.56  130.61  687.56  130.58  692.56  130.59
  697.56  130.66  702.56  130.74  707.56  130.84  712.56  130.85  717.56  130.83
  722.56  130.76  727.56  130.89  732.56  130.89  737.56  130.93  742.56  130.98
  747.56  131.03  752.56  130.98  757.56  131.07  762.56  131.08  767.56  131.12
  772.56  131.04  777.56  131.14  782.56  131.55  787.56  132.14  792.56  132.58
   795.1   132.6  797.56  132.63  802.55  132.63  807.55  132.63  812.55  132.63
  817.55  132.69  822.55  132.82  827.55  132.97  832.55  132.92
BR D #Mann= 9
       0     .15  335.29     .07  374.42     .04   389.1    .015  436.51     .04
  472.12    .015  527.57     .04  532.57     .07   795.1     .15
BC Design=,, 0 ,, 0 ,,,,,,
BC Use User HTab Curves=0
BC User HTab FreeFlow(D)= 0

Type RM Length L Ch R = 1 ,7745.163,87.97,84.86,82.21
BEGIN DESCRIPTION:
Downstream Section - GREENHOUSE RD
U20_200
END DESCRIPTION:
XS GIS Cut Line= 5
3013144.5772381113879669.81760173013156.2189471113879478.8911463
3013155.9561523613879364.22930213013162.2602736113879212.7236996
3013177.8498093613878838.0754988
#Sta/Elev= 30
       0  133.74   19.62  133.95  152.04   133.4  191.28  133.89  211.22  132.85
  226.18  132.89  236.15  133.59  261.08  134.12  335.29  134.21  359.75  133.61
  369.53  132.29  374.42  131.04  390.75  128.84  422.92  120.07  429.08  118.95
  436.51  114.14  472.12  115.07  478.29  116.33  483.32  118.63  488.29  119.63
  517.58  127.56  527.57  129.74  532.57  130.17  542.57  129.87  557.57  130.29
  662.56  130.42  772.56  131.04  777.56  131.14   795.1   132.6  832.55  132.92
#Mann= 5 ,-1 , 0
       0     .15       0  335.29     .07       0  374.42     .04       0
  532.57     .07       0   795.1     .15       0
#XS Ineff= 2 ,-1
       0  388.58   131.6  526.19  832.55   131.6
Permanent Ineff=
       F       F
Bank Sta=374.42,532.57
XS Rating Curve= 0 ,0
Exp/Cntr=0.5,0.3

Type RM Length L Ch R = 1 ,7660.303,133.73,117.8,101
Node Name=I
XS GIS Cut Line= 2
3013223.99997953 13879645.0000663013256.9999135313878864.9999856
#Sta/Elev= 30
       0  133.24  134.26  133.71   164.1  133.26  179.01  132.59  248.63  134.04
  334.23  133.14     363  132.97  372.94  130.77  392.84  129.46  397.81  128.74
   418.3  123.76  435.44  121.24  443.87  119.07  446.93  116.73  450.67   116.5
  453.99  116.64   461.5  119.26  482.12  121.51  512.18  128.52  522.12  129.23
  537.04   128.6  556.93  129.93  631.52  130.09  656.38   130.6  666.33  130.18
  701.14  130.81  745.89  130.45  766.48  131.01  775.72  132.21   780.7  132.24
#Mann= 5 ,-1 , 0
       0     .15       0  334.23     .07       0  372.94     .04       0
  522.12     .07       0  766.48     .15       0
#XS Ineff= 2 ,-1
       0  329.89   131.6  653.86   780.7   131.6
Permanent Ineff=
       F       F
Bank Sta=372.94,522.12
XS Rating Curve= 0 ,0
Exp/Cntr=0.3,0.1

Type RM Length L Ch R = 1 ,7542.502,177.63,181.81,182.34
XS GIS Cut Line= 3
3013503.9128055313879655.18410083013336.7891240313879101.4394733
3013336.8324310313878850.0521809
#Sta/Elev= 30
       0  132.68   74.79  131.54  114.69  133.07   144.6  132.51  214.41  133.63
  239.34  132.51  304.17  132.72  339.07  130.96     364  130.89  408.72  132.01
  428.82  132.18  443.78  129.78  453.76  129.66  463.73   128.7  490.05  122.08
  514.32  118.76  517.68  115.23  522.32  115.13  527.22  115.95  530.12   118.7
  554.78   123.1  578.41  129.01  598.13  127.78  612.92  129.32  632.64  129.89
  736.15  130.59  775.58  130.13  790.37   130.6  796.94  131.56   829.8  132.27
#Mann= 5 ,-1 , 0
       0     .15       0  408.72     .07       0  453.76     .04       0
  578.41     .07       0  796.94     .15       0
#XS Ineff= 1 ,-1
       0  255.48   131.6
Permanent Ineff=
       F
Bank Sta=453.76,578.41
XS Rating Curve= 0 ,0
Exp/Cntr=0.3,0.1

Type RM Length L Ch R = 1 ,7360.69 ,536.87,543.59,544.06
XS GIS Cut Line= 4
3013552.99997769 13879706.9999423013566.9999496913879265.9998398
3013528.0000276913879113.00014583013410.1928486113878621.4095935
#Sta/Elev= 30
       0  132.38   69.41  132.54  123.94  131.27  158.64  133.07  247.88   133.6
  342.07  132.13  376.77  129.89  426.35   132.3  498.46  132.22  515.23  132.27
  530.04  129.22   539.9  129.19  549.77  127.89  564.58  122.87   597.8  118.57
  601.13  115.91  605.72  115.23  610.76  115.98  614.08  118.59  628.85  120.11
  658.59  128.15  663.54  128.57  757.71  130.23  807.27  129.81  829.17  131.15
   916.3  131.57   960.9  128.97  985.68  129.02 1030.29  131.59 1104.62  132.75
#Mann= 5 ,-1 , 0
       0     .15       0  498.46     .07       0   539.9     .04       0
  663.54     .07       0  829.17     .15       0
#XS Ineff= 2 ,-1
       0  231.98   131.6 1028.81 1104.62   131.6
Permanent Ineff=
       F       F
Bank Sta=539.9,663.54
XS Rating Curve= 0 ,0
Exp/Cntr=0.3,0.1

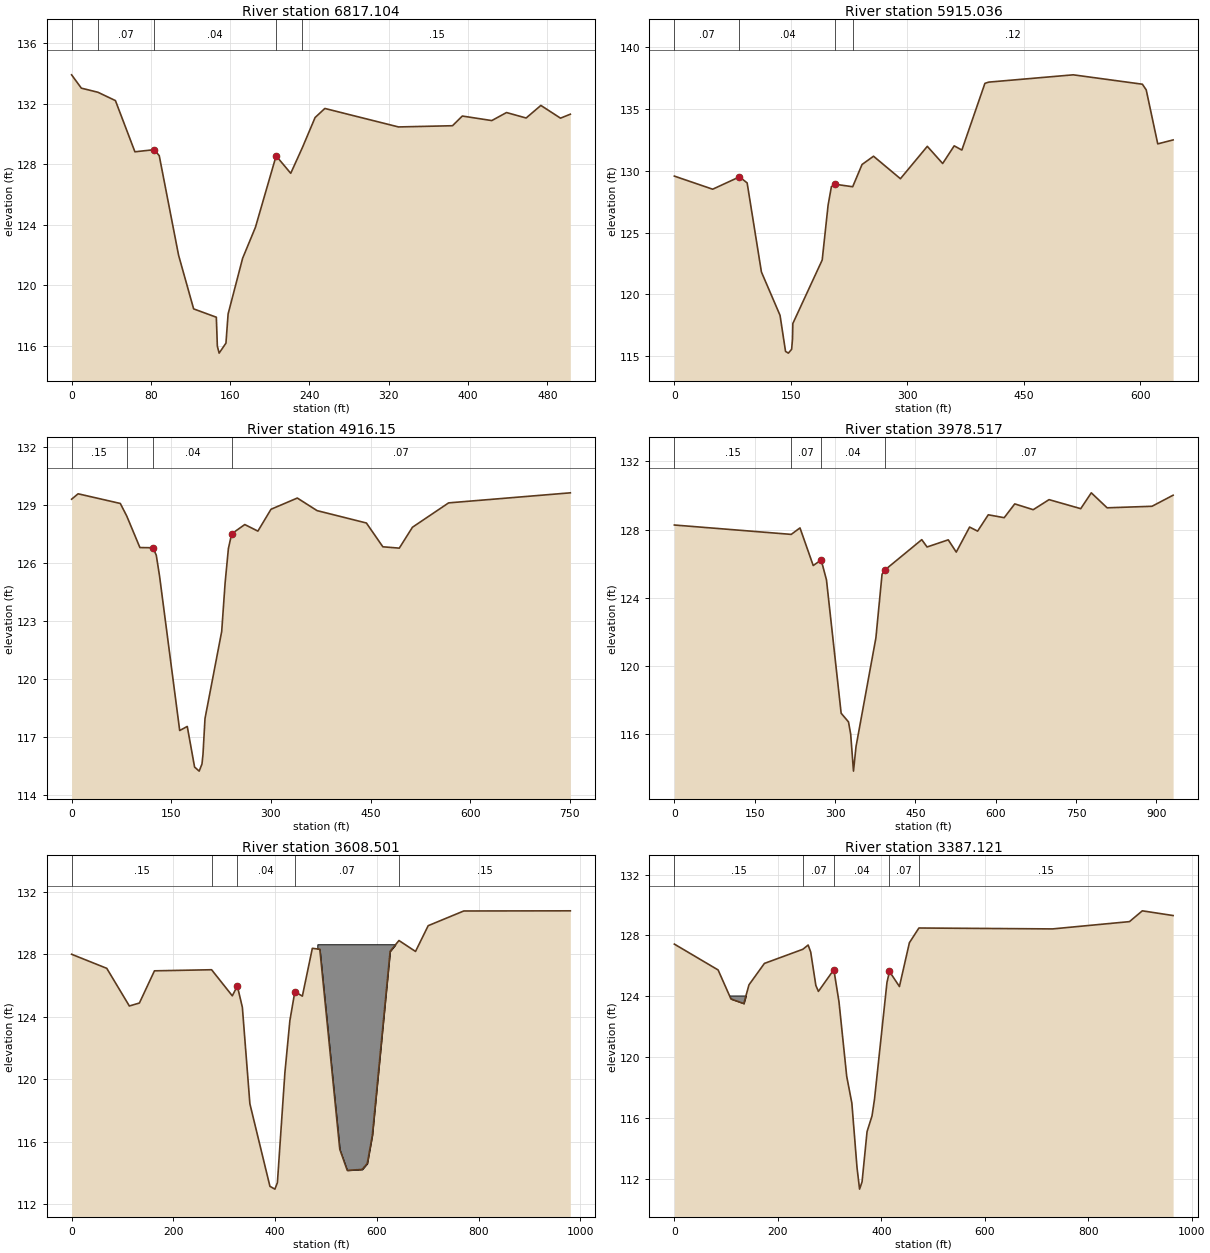
Type RM Length L Ch R = 1 ,6817.104,884.27,902.07,905.7
XS GIS Cut Line= 3
3014073.9999199513879146.00007983014037.9999919413878897.9999196
3014054.1699071113878645.8691903
#Sta/Elev= 30
       0   133.9    9.83  133.02   26.53  132.75   44.22   132.2   63.88  128.82
   83.53  128.96   88.45  128.56  107.96  121.99  123.15  118.45  146.05   117.9
  147.07  115.99  148.87  115.53  155.75  116.19  157.94  118.12  172.57  121.79
  185.47  123.83  206.38  128.55  221.12   127.4  232.97  129.11  245.69  131.08
  255.55  131.68  329.86  130.46  384.35  130.54  394.26  131.18  423.99  130.88
  438.85  131.41  458.66  131.05  473.53  131.88  493.34  131.04  503.25   131.3
#Mann= 5 ,-1 , 0
       0     .12       0   26.53     .07       0   83.53     .04       0
  206.38     .07       0  232.97     .15       0
Bank Sta=83.53,206.38
XS Rating Curve= 0 ,0
Exp/Cntr=0.3,0.1

Type RM Length L Ch R = 1 ,5915.036,993.92,998.89,991.81
XS GIS Cut Line= 4
3014937.0001624413879190.99998983014954.0001284513878934.9998456
3014981.0000744513878549.99995943014981.0000744513878549.9999594
#Sta/Elev= 30
       0  129.58   49.34  128.52   83.88  129.52   93.74  129.03  112.13  121.82
  136.11  118.31  143.21  115.39  146.84  115.25  151.04  115.56  152.17  116.37
  152.63  117.65  190.44  122.79  198.01  127.22  202.29  128.73  207.22  128.92
  229.71  128.72  241.76  130.52  256.56  131.19   291.2  129.37  325.84  131.99
  345.63   130.6  360.47  132.03  370.37  131.69  400.06  137.09     405  137.19
  513.86  137.78  602.92  137.02  607.87  136.56  622.72  132.19  642.51  132.51
#Mann= 4 ,-1 , 0
       0     .07       0   83.88     .04       0  207.22     .07       0
  229.71     .12       0
Bank Sta=83.88,207.22
XS Rating Curve= 0 ,0
Exp/Cntr=0.3,0.1

Type RM Length L Ch R = 1 ,4916.15 ,949.17,937.63,923.74
Node Name=H
XS GIS Cut Line= 4
3015932.0001409513879247.99987583015936.0001329513879165.0000418
3015942.0001209413878948.00014773015918.9998388613878498.0000634
#Sta/Elev= 30
       0  129.28    9.78  129.56   73.32  129.06   83.02  128.41  102.83  126.78
  122.57  126.77   127.5  126.38  132.43   125.3  162.72  117.32  174.11  117.53
  185.15  115.43  192.06  115.22  196.27  115.59   197.8  116.09  200.82  117.94
  225.94  122.44  231.11  124.96  236.04  126.73  240.97  127.49  260.71  127.97
  280.44  127.63  300.18  128.76  339.79  129.34   369.5  128.69  443.77  128.05
  468.53  126.82  493.29  126.75  513.09  127.83  567.56  129.09  750.77  129.61
#Mann= 4 ,-1 , 0
       0     .15       0   83.02     .07       0  122.57     .04       0
  240.97     .07       0
Bank Sta=122.57,240.97
XS Rating Curve= 0 ,0
Exp/Cntr=0.3,0.1

Type RM Length L Ch R = 1 ,3978.517,347.88,370.02,367.09
XS GIS Cut Line= 5
3016970.0000334413879379.99993993016914.0001454513879234.9999018
3016826.9999913613878894.99992563016801.0000433613878804.0001076
3016773.0000993613878475.0001094
#Sta/Elev= 30
       0  128.27  218.18  127.72  234.53   128.1  259.24  125.89  274.07  126.22
  283.96  125.05  311.38  117.22  325.09  116.71  329.12  116.01  334.43  113.82
  339.14  115.26  376.25  121.64  387.76  125.38   392.7  125.62  461.91  127.41
  471.79  126.98  511.37   127.4  526.32  126.68  551.22  128.15  566.17  127.91
  586.09  128.87  615.82   128.7  635.53  129.51  670.03  129.17   699.6  129.76
  758.74  129.23  778.45  130.16  808.02  129.28   891.8  129.37  931.22  130.02
#Mann= 4 ,-1 , 0
       0     .15       0  218.18     .07       0  274.07     .04       0
   392.7     .07       0
Bank Sta=274.07,392.7
XS Rating Curve= 0 ,0
Exp/Cntr=0.3,0.1

Type RM Length L Ch R = 1 ,3608.501,217.99,221.38,220.33
Node Name=G
XS GIS Cut Line= 4
3017217.9998655313879325.00004993017205.9998895213878950.0001437
3017197.9999055313878753.99987953017207.9998855313878345.0000414
#Sta/Elev= 30
       0     128   69.11   127.1  113.54  124.69  133.29  124.88  162.91  126.94
  275.22  127.01  315.95  125.34  325.82  125.97   335.7  124.61  350.51  118.43
   389.9  113.15  399.71  112.97  404.62  113.39  419.33  120.42  429.14  123.76
  438.94  125.61  453.66  125.32  473.27  128.38  487.99  128.32  527.22  115.52
  541.93  114.17  571.36  114.23  581.33  114.61  591.31  116.43  626.24  128.19
  643.59  128.88  676.13  128.18  701.08  129.83  770.93  130.77  980.48  130.78
#Mann= 5 ,-1 , 0
       0     .15       0  275.22     .07       0  325.82     .04       0
  438.94     .07       0  643.59     .15       0
#Block Obstruct= 1 ,-1
  483.08  636.22  128.64
Bank Sta=325.82,438.94
XS Rating Curve= 0 ,0
Exp/Cntr=0.3,0.1

Type RM Length L Ch R = 1 ,3387.121,507.72,515.89,511.72
XS GIS Cut Line= 4
3017421.0001156913879307.00008583017425.0001076913878949.0001457
 3017423.000111713878819.0000776 3017468.000021713878345.0000414
#Sta/Elev= 30
       0  127.43   84.53  125.73   109.4  123.82  134.26  123.52   144.2  124.75
  174.04  126.16  248.38  127.09  258.57  127.37  263.54  126.91  273.49  124.71
  278.46  124.32   308.3  125.75  318.24  123.63  333.16  118.73   343.1  116.97
  353.05  112.74  358.02  111.31  362.84  111.79  372.47  115.09   382.1  116.13
  386.91  117.23  410.99  124.91  415.81  125.63  435.07  124.64  454.33  127.52
  472.73  128.49  731.06  128.43  879.85  128.91  904.65  129.62  964.17  129.31
#Mann= 5 ,-1 , 0
       0     .15       0  248.38     .07       0   308.3     .04       0
  415.81     .07       0  472.73     .15       0
#Block Obstruct= 1 ,-1
  104.42  139.23  124.05
Bank Sta=308.3,415.81
XS Rating Curve= 0 ,0
Exp/Cntr=0.3,0.1

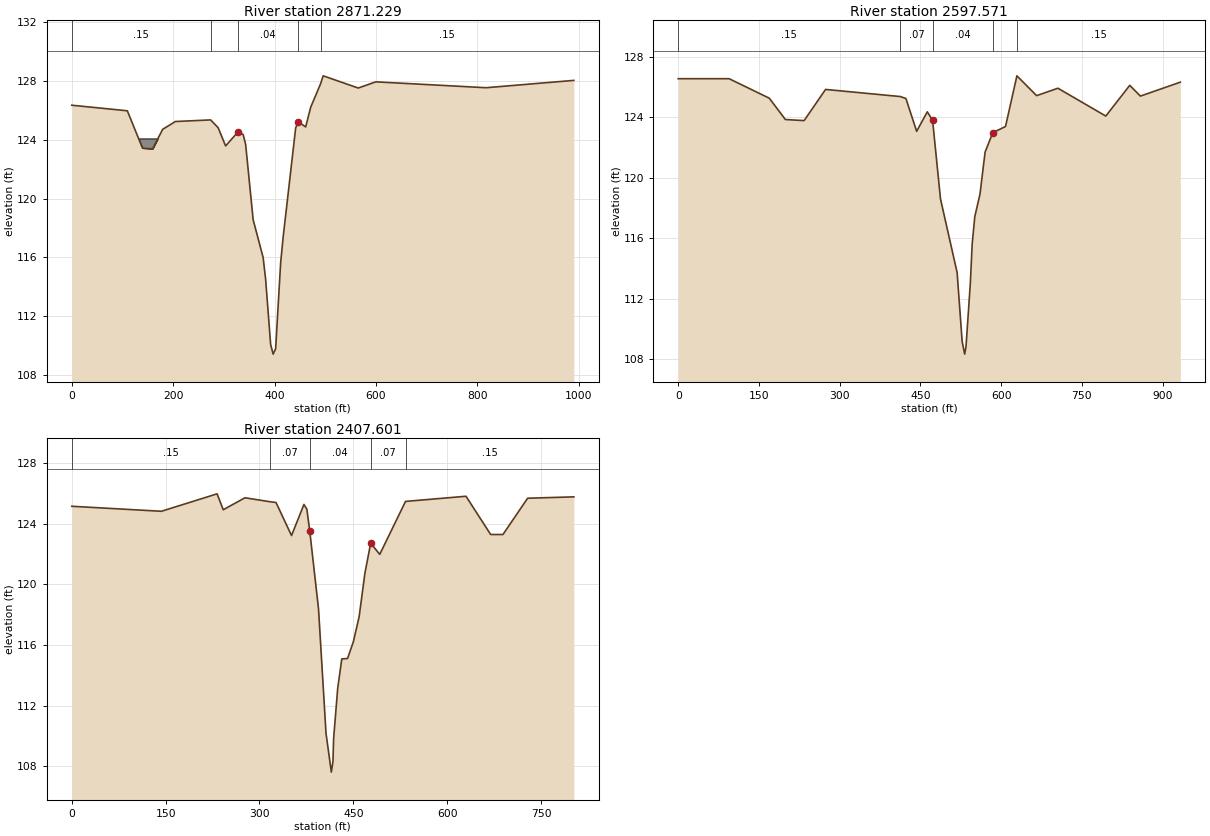
Type RM Length L Ch R = 1 ,2871.229,270.71,273.66,268.92
XS GIS Cut Line= 4
3017922.0000979513879352.99999383017928.0000859513879093.9998557
3017940.0000619413878813.00008963017991.9999579513878365.9999994
#Sta/Elev= 30
       0  126.35  109.61  125.97   139.5  123.43  159.43  123.38  179.36  124.71
  204.27  125.24  273.92  125.35  288.68  124.82  303.48  123.58  328.15  124.54
  338.02  124.36  342.95  123.69  357.76  118.56  377.49  115.98  382.43  114.49
   392.3  110.06  397.23  109.41  402.16  109.78  412.03  115.63  416.97  117.38
  441.64   124.8  446.57  125.23  461.38  124.87  471.24  126.21   490.7   127.8
  495.92  128.35  565.05  127.52  599.67  127.94  817.26  127.54  990.34  128.04
#Mann= 5 ,-1 , 0
       0     .15       0  273.92     .07       0  328.15     .04       0
  446.57     .07       0   490.7     .15       0
#Block Obstruct= 1 ,-1
  129.53  169.39  124.09
Bank Sta=328.15,446.57
XS Rating Curve= 0 ,0
Exp/Cntr=0.3,0.1

Type RM Length L Ch R = 1 ,2597.571,180.07,189.97,183.22
XS GIS Cut Line= 5
3018140.9999880213879499.00002993018200.9998680213879044.9999537
3018202.9998640313878947.00014973018208.9998520313878857.0000016
 3018271.000056113878576.9999054
#Sta/Elev= 30
       0  126.56   94.58  126.56  169.24  125.27  199.11  123.86  233.95  123.79
  273.77  125.85  412.56  125.38   423.1  125.25  443.01  123.08  462.85  124.37
  472.65   123.8  487.35  118.61  518.24  113.74  527.58  109.19  532.24  108.35
  534.74  108.84  542.79  113.04  546.17  115.61  551.07  117.44  560.72  118.93
  570.21  121.71  584.45  122.99  608.19   123.4  629.31  126.75  665.95  125.44
   705.5  125.93   794.5  124.09     839  126.12  858.78  125.41  932.95  126.33
#Mann= 5 ,-1 , 0
       0     .15       0  412.56     .07       0  472.65     .04       0
  584.45     .07       0  629.31     .15       0
Bank Sta=472.65,584.45
XS Rating Curve= 0 ,0
Exp/Cntr=0.3,0.1

Type RM Length L Ch R = 1 ,2407.601,307.92,311.59,294.3
XS GIS Cut Line= 6
3018385.0001561913879413.99987193018379.9998381113879167.0000378
3018379.9998381113879042.99995773018385.0001561913878992.0000597
 3018387.000152213878931.9998516 3018382.000162213878612.0001635
#Sta/Elev= 30
       0  125.14  143.29  124.81  232.23  125.96  242.11  124.91  276.81   125.7
  316.54  125.44  326.41  125.39  351.21  123.21  371.05  125.26  375.71  124.95
  380.37  123.49  394.34  118.38  406.31  110.18  414.84  107.62  417.45  108.33
   418.4   109.8  424.98  113.14  431.53  115.08  440.77  115.11     450  116.21
  459.24  117.86  468.47  120.73  477.71  122.71  492.18  121.97  533.38  125.46
  630.04   125.8  669.43  123.28  689.12  123.28  728.51  125.67  802.37  125.76
#Mann= 5 ,-1 , 0
       0     .15       0  316.54     .07       0  380.37     .04       0
  477.71     .07       0  533.38     .15       0
Bank Sta=380.37,477.71
XS Rating Curve= 0 ,0
Exp/Cntr=0.3,0.1