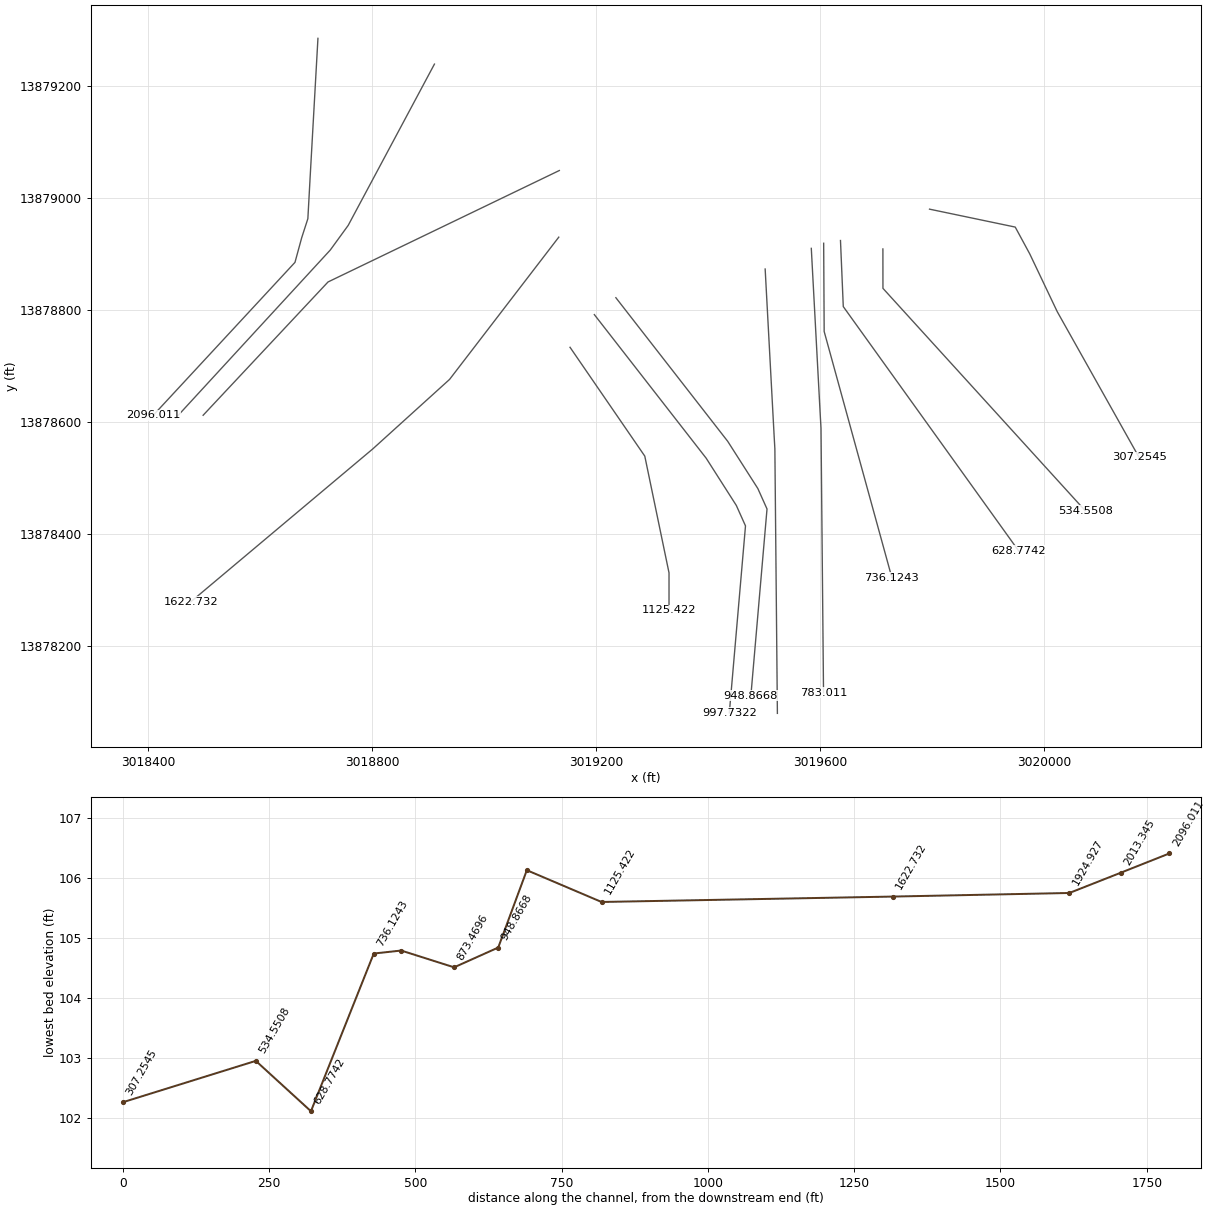
HEC-RAS study U120-00-00.prj: U120-00-00 2019 (Re-Study)

--- U120-00-00.g01 (geometry) --- (continued)

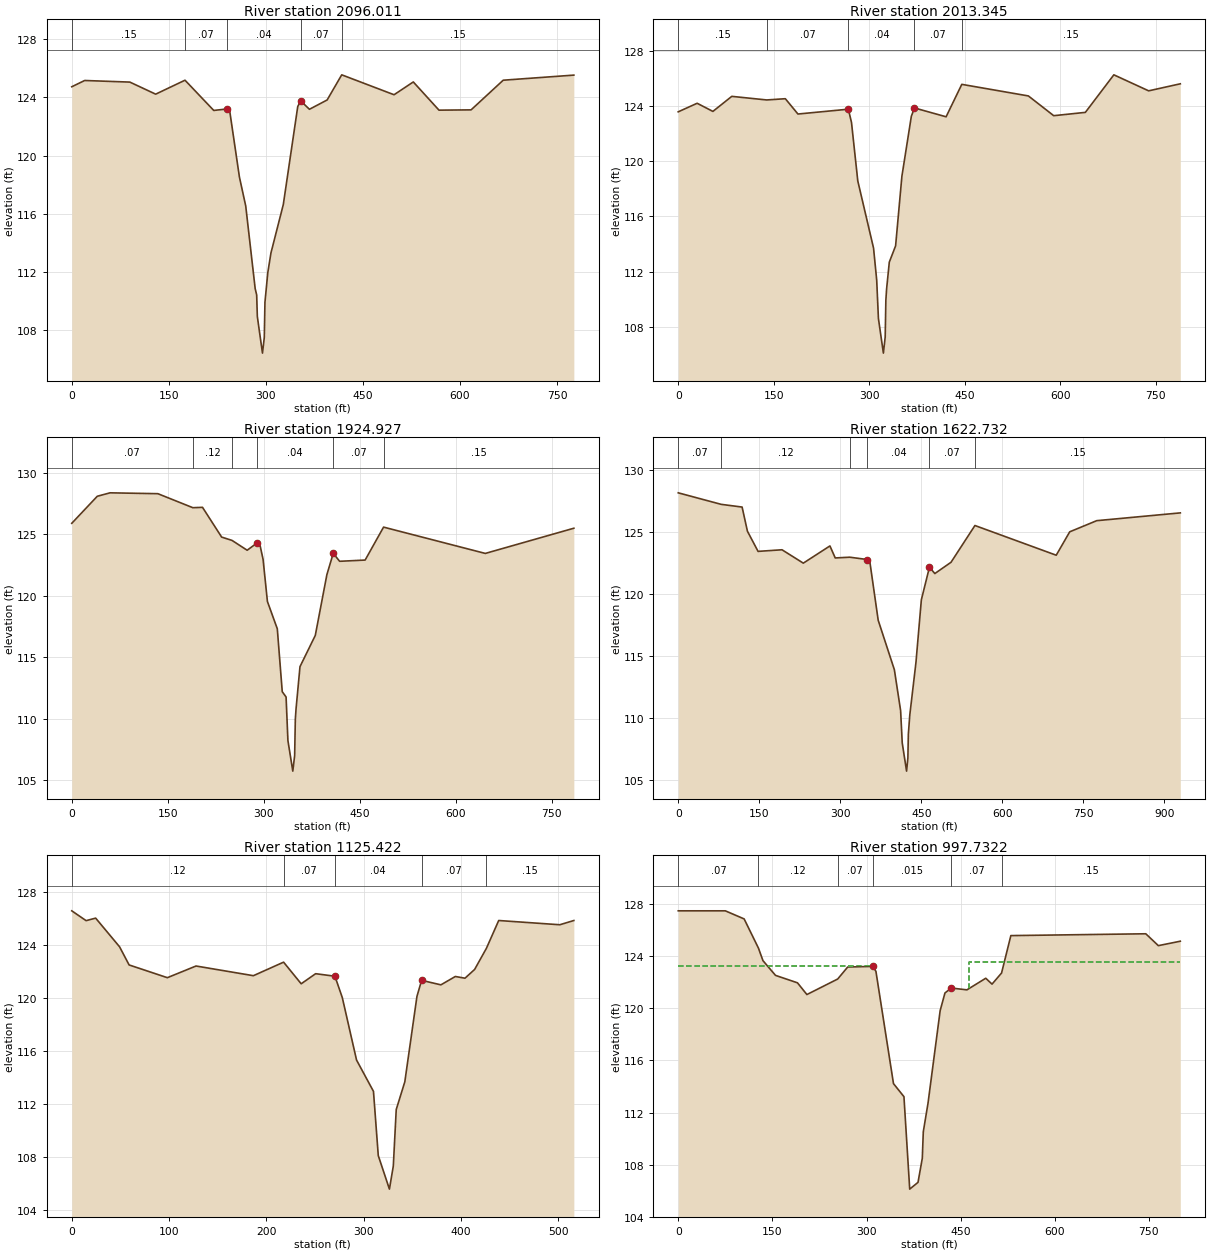
Type RM Length L Ch R = 1 ,2096.011,99.86,82.67,64.51
Node Name=F
XS GIS Cut Line= 6
3018702.9998482813879285.00012983018688.9998762813879035.9999717
3018684.9998842813878963.00011773018673.9999062713878928.9998576
3018661.9999302813878884.9999456 3018409.000108213878612.0001635
#Sta/Elev= 30
       0  124.73   19.95  125.16   89.78  125.05  129.68  124.22  175.03  125.18
  219.47   123.1  239.42   123.2  244.41  122.98  259.14  118.52  268.89  116.53
  283.51  110.84  285.82  110.41  286.82  108.93  294.78  106.41  297.57  107.48
  298.59   109.9  303.01  111.95  307.88   113.3  326.97  116.63   349.3  123.37
  353.77  123.76  367.36  123.18  394.72  123.82  417.28  125.55  498.14  124.18
  527.91  125.06  567.62  123.12  617.24  123.14  666.87  125.18  776.05  125.53
#Mann= 5 ,-1 , 0
       0     .15       0  175.03     .07       0  239.42     .04       0
  353.77     .07       0  417.28     .15       0
Bank Sta=239.42,353.77
XS Rating Curve= 0 ,0
Exp/Cntr=0.3,0.1

Type RM Length L Ch R = 1 ,2013.345,115.41,88.42,68.1
XS GIS Cut Line= 4
3018911.0000884413879238.99989383018757.0000683713878951.0001417
3018725.0001323713878906.99990163018449.0000281913878606.9998454
#Sta/Elev= 30
       0  123.57   29.69  124.19   54.43   123.6   84.12  124.69  138.99  124.43
  168.24  124.52  188.04  123.41  267.21  123.76  272.16   122.8  282.05  118.56
  306.79   113.7  311.74  111.38  314.45   108.6  322.25  106.09  325.09  107.26
  326.13  109.92  327.24  110.71  331.53  112.68  341.43  113.86  351.32   118.9
  366.16  123.25   371.1  123.85  420.76  123.21  445.41  125.56  550.02  124.72
  589.79  123.29   639.5  123.53  684.24  126.25  738.93  125.09  788.64   125.6
#Mann= 5 ,-1 , 0
       0     .15       0  138.99     .07       0  267.21     .04       0
   371.1     .07       0  445.41     .15       0
Bank Sta=267.21,371.1
XS Rating Curve= 0 ,0
Exp/Cntr=0.3,0.1

Type RM Length L Ch R = 1 ,1924.927,281.89,302.2,312.64
XS GIS Cut Line= 3
3019133.9999705313879048.99994573018721.0001403513878850.0000156
3018497.9999301913878612.0001635
#Sta/Elev= 30
       0  125.91   39.86  128.11    59.8  128.39  134.54  128.32  189.21  127.18
  204.31  127.21   234.2  124.79  250.41  124.52  274.07  123.72  289.02  124.29
     294  124.17  298.98  122.97  305.74  119.55  321.19  117.33  328.92  112.21
  334.91  111.78  337.77  108.24  345.41  105.75   348.3  107.02  349.36  109.96
  350.49  110.82  356.64  114.25  380.56  116.79  398.65  121.73  408.61  123.47
  418.58  122.82  458.44  122.92  487.25   125.6  646.23  123.46  784.59  125.51
#Mann= 6 ,-1 , 0
       0     .07       0  189.21     .12       0  250.41     .07       0
  289.02     .04       0  408.61     .07       0  487.25     .15       0
Bank Sta=289.02,408.61
XS Rating Curve= 0 ,0
Exp/Cntr=0.3,0.1

Type RM Length L Ch R = 1 ,1622.732,441.35,497.31,528.72
Node Name=E
XS GIS Cut Line= 4
3019132.9999725213878929.99985563018938.0000344413878676.0000355
3018800.9999803613878551.99995543018475.9999741913878278.9998453
#Sta/Elev= 30
       0  128.17   79.44  127.24  118.24  127.02  128.09  125.07  147.79  123.44
  192.13  123.57  231.54  122.49  280.81  123.88  290.66  122.91  317.62  122.97
  350.18  122.78  355.18  122.46  370.16  117.88  400.13  113.88  411.67  110.58
  414.67  107.97  422.71  105.69  425.12  106.75     426  108.68  428.66  110.22
  440.08  114.47  450.07  119.53  465.05  122.16  475.04  121.65     505  122.56
  549.26  125.53  699.75  123.13  724.72  125.02  774.65  125.92  929.45  126.55
#Mann= 6 ,-1 , 0
       0     .07       0   79.44     .12       0  317.62     .07       0
  350.18     .04       0  465.05     .07       0  549.26     .15       0
Bank Sta=350.18,465.05
XS Rating Curve= 0 ,0
Exp/Cntr=0.3,0.1

Type RM Length L Ch R = 1 ,1125.422,109.7,127.69,140.12
Node Name=D
XS GIS Cut Line= 4
 3019153.096717113878733.35654813019286.5633136913878539.0872516
3019329.8420985313878330.69101493019329.8420985313878263.3984985
#Sta/Elev= 30
       0  126.58   14.73  125.84   24.55  126.03    49.1  123.87   58.92   122.5
   98.21  121.54  127.67  122.42  186.59  121.69  217.64  122.71   235.7  121.08
  250.55  121.84  270.35  121.65  277.94  120.04  292.59  115.33  309.97  112.97
   314.9  108.13  326.35   105.6  330.35  107.34  333.35   111.6  342.17  113.69
  354.64  120.13  359.44  121.34  379.24     121  394.09  121.63  403.99   121.5
  413.89  122.16  425.98  123.75  438.64  125.85  501.41  125.53  515.83  125.85
#Mann= 5 ,-1 , 0
       0     .12       0  217.64     .07       0  270.35     .04       0
  359.44     .07       0  425.98     .15       0
Bank Sta=270.35,359.44
XS Rating Curve= 0 ,0
Exp/Cntr=0.5,0.3

Type RM Length L Ch R = 1 ,997.7322,49.56,48.87,49.16
BEGIN DESCRIPTION:
Upstream Section - WEIR U/S OF BARKER CYPRESS
END DESCRIPTION:
XS GIS Cut Line= 6
3019196.5274045313878791.69304563019396.2186061913878535.2785322
3019423.1175025313878493.13032253019450.0163988613878450.9824409
3019466.3949750213878414.48940373019437.5436547713878080.7341657
#Sta/Elev= 30
       0  127.47      75  127.47     105  126.85  127.82  124.61     135  123.65
     155  122.52     190  121.95     205  121.05  254.07  122.24     270  123.16
     310  123.21     315  122.83  342.98  114.22  359.65  113.22  368.83  106.13
  382.07  106.65   388.9   108.5  390.48  110.53     398  112.72  417.35  119.82
     425  121.17     435  121.55     460  121.41     490   122.3     500  121.85
  515.17   122.7     530  125.57     745  125.71     765   124.8     800  125.14
#Mann= 6 ,-1 , 0
       0     .07       0  127.82     .12       0  254.07     .07       0
     310    .015       0     435     .07       0  515.17     .15       0
#XS Ineff= 2 ,-1
       0     305  123.25  462.53     800  123.57
Permanent Ineff=
       F       F
Bank Sta=310,435
XS Rating Curve= 0 ,0
Exp/Cntr=0.5,0.3

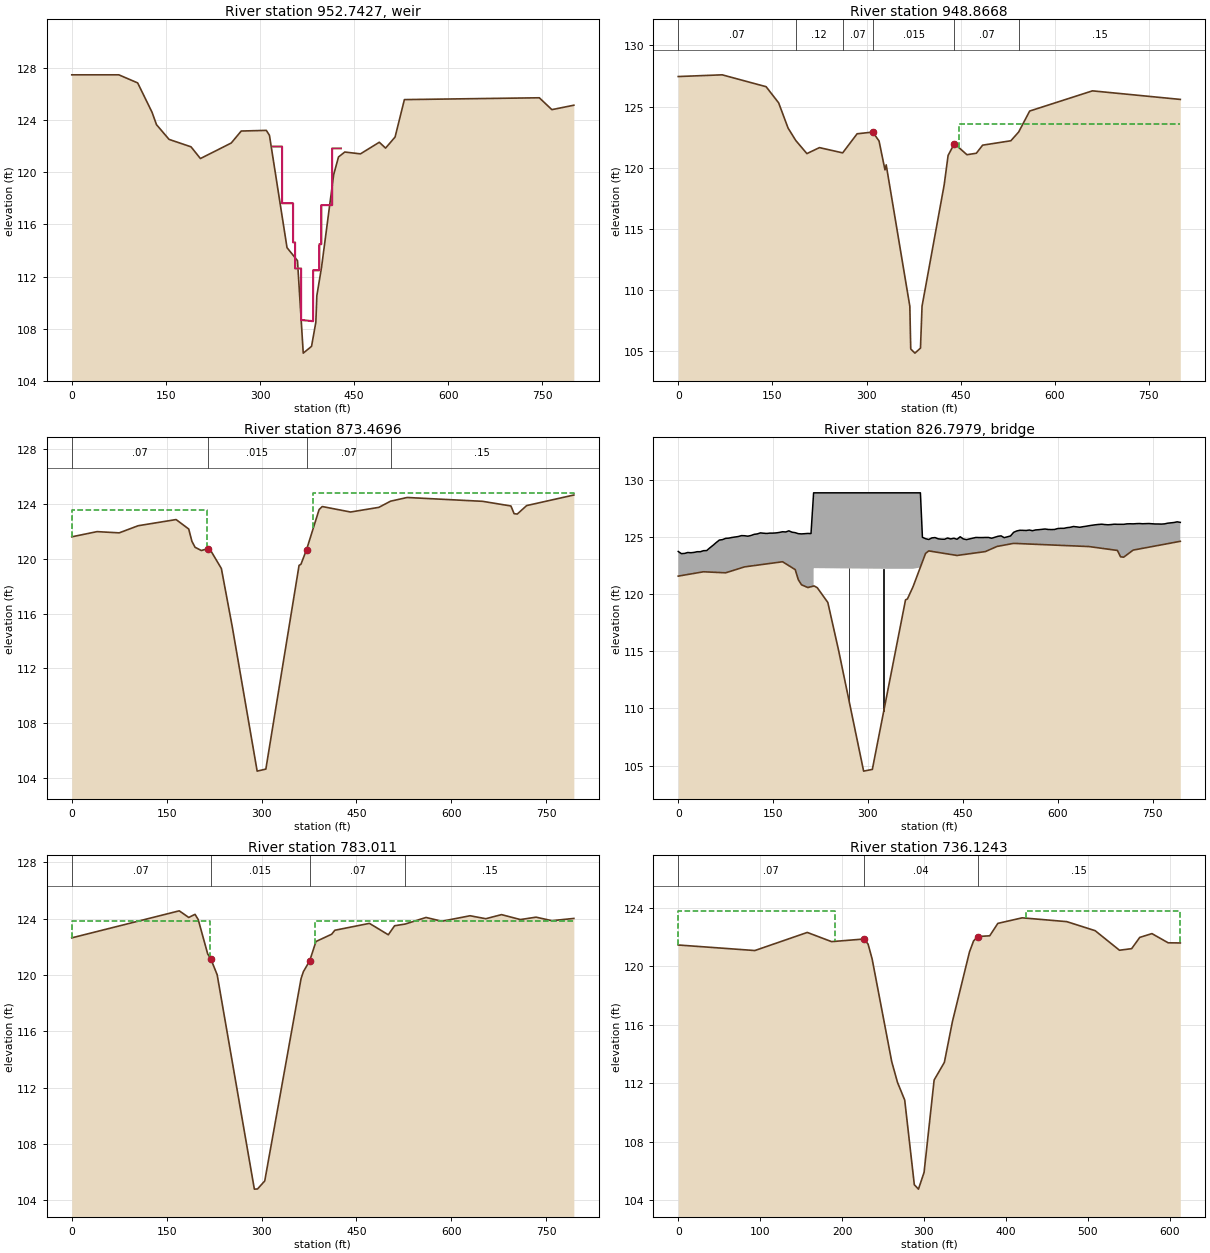
Type RM Length L Ch R = 5 ,952.7427,,,
BEGIN DESCRIPTION:
WEIR U/S OF BARKER CYPRESS
END DESCRIPTION:
Node Name=WEIR US BARKER
IW Pilot Flow=0
#Inline Weir SE= 18
  320.06  121.97  335.06  121.97  335.07  117.62  352.57  117.62  352.58  114.62
  355.78  114.62  355.79  112.62  365.39  112.62   365.4  108.67   384.6  108.58
  384.61  112.48  394.46  112.48  394.47  114.48  397.62  114.48  397.63  117.48
  414.83  117.48  414.84  121.83  428.74  121.83
IW Dist,WD,Coef,Skew,MaxSub,Min_El,Is_Ogee,SpillHt,DesHd
44.5,2,2.6,0,0.98,, 0 ,,,0,0,

Type RM Length L Ch R = 1 ,948.8668,111.6,75.4,37.74
BEGIN DESCRIPTION:
Downstream Section - WEIR U/S OF BARKER CYPRESS
END DESCRIPTION:
XS GIS Cut Line= 6
3019234.9544930313878821.87900893019434.6456946913878565.4644954
3019461.5445910213878523.31628583019488.4434873613878481.1684042
3019504.8220635213878444.67536693019475.9707432813878110.9201289
#Sta/Elev= 30
       0  127.45      70  127.59     140  126.62     160   125.3     175  123.24
  187.18  122.23     205  121.15     225  121.64     262  121.21     285  122.77
     310  122.91     320  122.18  329.42  119.82  331.38  120.23  369.02  108.67
  370.46  105.18  377.15  104.84  385.98  105.25  388.49  108.68  423.81  118.61
     430     121     440  121.97     460  121.06     475  121.18     485  121.84
     530   122.2  542.36  122.91     560  124.63     660  126.28     800  125.58
#Mann= 6 ,-1 , 0
       0     .07       0  187.18     .12       0     262     .07       0
     310    .015       0     440     .07       0  542.36     .15       0
#XS Ineff= 2 ,-1
       0     310  122.91  447.74     800  123.57
Permanent Ineff=
       F       F
Bank Sta=310,440
XS Rating Curve= 0 ,0
Exp/Cntr=0.5,0.3

Type RM Length L Ch R = 1 ,873.4696,93.34,90.46,93.81
BEGIN DESCRIPTION:
Upstream Section - BARKER CYPRESS ROAD
U20_100
END DESCRIPTION:
Node Name=C
XS GIS Cut Line= 4
 3019501.509734213878873.08559933019517.6051744413878573.6363951
3019518.8456575313878552.08558523019523.3466327813878079.7115299
#Sta/Elev= 30
       0   121.6   39.98  121.98   74.97  121.89  104.96  122.41  164.93  122.86
  184.93  122.17  189.92  121.28  194.92  120.84  204.92   120.6  214.92  120.74
  219.91  120.58  236.54  119.29  253.62  115.08  293.14  104.51  306.89  104.66
   359.4  119.52  362.39   119.6  371.19  120.66  391.08  123.59  396.06  123.81
  440.81  123.41  485.56  123.75  504.04   124.2  530.32  124.47  649.66  124.19
  694.41  123.85  699.38  123.29  704.36  123.26  719.27  123.88  793.86  124.65
#Mann= 4 ,-1 , 0
       0     .07       0  214.92    .015       0  371.19     .07       0
  504.04     .15       0
#XS Ineff= 2 ,-1
       0  214.03  123.57  381.71  793.86  124.81
Permanent Ineff=
       F       F
Bank Sta=214.92,371.19
XS Rating Curve= 0 ,0
Exp/Cntr=0.5,0.3

Type RM Length L Ch R = 3 ,826.7979,,,
BEGIN DESCRIPTION:
BARKER CYPRESS ROAD
U20_100
END DESCRIPTION:
Node Name=BARKER CYPRESS
Bridge Culvert--1,0,-1,-1, 0
Deck Dist Width WeirC Skew NumUp NumDn MinLoCord MaxHiCord MaxSubmerge Is_Ogee
7,83,2.6,0, 131, 133, , , 0.98, 0, 0,0,,
       0       5      10   14.99   19.99   24.99   29.99   34.99   39.98   44.98
   49.98   54.98   59.98   64.97   69.97   74.97   79.97   84.97   89.96   94.96
   99.96  104.96  109.96  114.95  119.95  124.95  129.95  134.95  139.94  144.94
  149.94  154.94  159.94  164.93  169.93  174.93  179.93  184.93  189.92  194.92
  199.92  204.92  209.92 214.031 214.435  328.85 382.717 382.925  386.11  391.08
  396.06  401.03     406  410.97  415.95  420.92  425.89  430.86  435.84  440.81
  445.78  450.76  455.73   460.7  465.67  470.65  475.62  480.59  485.56  490.54
  495.51  500.48  505.45  510.43   515.4  520.37  525.34  530.32  535.29  540.26
  545.23  550.21  555.18  560.15  565.12   570.1  575.07  580.04  585.01  589.99
  594.96  599.93  604.91  609.88  614.85  619.82   624.8  629.77  634.74  639.71
  644.69  649.66  654.63   659.6  664.58  669.55  674.52  679.49  684.47  689.44
  694.41  699.38  704.36  709.33   714.3  719.27  724.25  729.22  734.19  739.17
  744.14  749.11  754.08  759.06  764.03     769  773.97  778.95  783.92  788.89
  793.86
  123.76  123.57  123.59  123.67  123.65  123.68  123.74  123.74  123.83  123.84
  124.08   124.3  124.54  124.76   124.8  124.91  124.93  124.99  125.03  125.07
  125.15  125.14   125.1  125.16  125.26   125.3  125.39  125.36  125.34  125.37
  125.37  125.39  125.43  125.49  125.47  125.57  125.45  125.41  125.32   125.3
  125.32  125.34  125.33   128.9   128.9   128.9   128.9   128.9     125  124.88
  124.81  124.95  124.98  124.87  124.84  124.83  124.94  124.86  124.92  124.83
  125.05  124.86   124.8  124.86  124.92  124.99  124.98  124.98  124.99  124.99
  124.92  125.01  125.09  125.13  124.97  125.04  125.12  125.44  125.56  125.62
  125.61   125.6  125.64  125.58  125.65  125.67   125.7  125.73  125.69  125.68
  125.69  125.77  125.79  125.79  125.85  125.88  125.95  125.92  125.88  125.93
  125.97  126.02  126.06   126.1  126.13  126.15  126.12   126.1  126.12  126.15
  126.14  126.14  126.14  126.18  126.19  126.18   126.2  126.21  126.19   126.2
  126.21  126.19  126.17  126.17  126.16  126.18  126.24  126.27   126.3  126.36
  126.31
                                                                                
                                                                                
                                                                                
                                                                                
                           122.2   122.3  122.24  122.24  122.17
                                                                                
                                                                                
                                                                                
                                                                                
                                                                                
                                                                                
                                                                                
                                                                                
        
       0       5      10   14.99   19.99   24.99   29.99   34.99   39.98   44.98
   49.98   54.98   59.98   64.97   69.97   74.97   79.97   84.97   89.96   94.96
   99.96  104.96  109.96  114.95  119.95  124.95  129.95  134.95  139.94  144.94
  149.94  154.94  159.94  164.93  169.93  174.93  179.93  184.93  189.92  194.92
  199.92  204.92  209.92  214.92 218.812 219.177 219.909  276.42 334.006 387.712
 388.202  391.08  396.06  401.03     406  410.97  415.95  420.92  425.89  430.86
  435.84  440.81  445.78  450.76  455.73   460.7  465.67  470.65  475.62  480.59
  485.56  490.54  495.51  500.48  505.45  510.43   515.4  520.37  525.34  530.32
  535.29  540.26  545.23  550.21  555.18  560.15  565.12   570.1  575.07  580.04
  585.01  589.99  594.96  599.93  604.91  609.88  614.85  619.82   624.8  629.77
  634.74  639.71  644.69  649.66  654.63   659.6  664.58  669.55  674.52  679.49
  684.47  689.44  694.41  699.38  704.36  709.33   714.3  719.27  724.25  729.22
  734.19  739.17  744.14  749.11  754.08  759.06  764.03     769  773.97  778.95
  783.92  788.89  793.86
  123.76  123.57  123.59  123.67  123.65  123.68  123.74  123.74  123.83  123.84
  124.08   124.3  124.54  124.76   124.8  124.91  124.93  124.99  125.03  125.07
  125.15  125.14   125.1  125.16  125.26   125.3  125.39  125.36  125.34  125.37
  125.37  125.39  125.43  125.49  125.47  125.57  125.45  125.41  125.32   125.3
  125.32  125.34  125.33  125.32  128.95   128.9  128.95  128.95  128.95  128.95
  128.95  124.88  124.81  124.95  124.98  124.87  124.84  124.83  124.94  124.86
  124.92  124.83  125.05  124.86   124.8  124.86  124.92  124.99  124.98  124.98
  124.99  124.99  124.92  125.01  125.09  125.13  124.97  125.04  125.12  125.44
  125.56  125.62  125.61   125.6  125.64  125.58  125.65  125.67   125.7  125.73
  125.69  125.68  125.69  125.77  125.79  125.79  125.85  125.88  125.95  125.92
  125.88  125.93  125.97  126.02  126.06   126.1  126.13  126.15  126.12   126.1
  126.12  126.15  126.14  126.14  126.14  126.18  126.19  126.18   126.2  126.21
  126.19   126.2  126.21  126.19  126.17  126.17  126.16  126.18  126.24  126.27
   126.3  126.36  126.31
                                                                                
                                                                                
                                                                                
                                                                                
                                   122.2   122.2   122.2  122.18  122.19  122.23
  122.23
                                                                                
                                                                                
                                                                                
                                                                                
                                                                                
                                                                                
                                                                                
                        
Pier Skew, UpSta & Num, DnSta & Num=  ,270, 2 ,270, 2 , 0 , 0 , 0 ,,
    1.35    1.35
     102     124
    1.35    1.35
     102     124
Pier Skew, UpSta & Num, DnSta & Num=  ,325, 2 ,325, 2 , 0 , 0 , 0 ,,
    1.35    1.35
     102     124
    1.35    1.35
     102     124
Abutment Skew #Up #Dn= , 4 , 4
  214.02  214.03  238.08  288.28
   122.2   122.2  119.29  105.77
   218.8  218.81  241.29     296
   122.2   122.2  119.29  104.79
Abutment Skew #Up #Dn= , 3 , 3
  314.14  361.17  382.92
  105.72  119.52  122.17
  312.44  366.28   388.2
  105.37  118.88  122.23
BR Coef=-1 , 1 , 1 ,0.9, 0 ,,,0.8,-1,1.2,0,
WSPro=,,,, 1 ,,,, 0 ,,,, 0 ,,,,-1 ,-1 ,-1 , 0 , 0 , 0 , 0 , 0
BC Design=,, 0 ,, 0 ,,,,,,
BC Use User HTab Curves=0
BC User HTab FreeFlow(D)= 0

Type RM Length L Ch R = 1 ,783.011 ,33.8,46.89,62.59
BEGIN DESCRIPTION:
Downstream Section - BARKER CYPRESS ROAD
U20_100
END DESCRIPTION:
XS GIS Cut Line= 4
3019583.8842413613878910.00284843019599.9796816113878610.5536441
3019601.2201646913878589.00283423019605.7211399413878116.6287789
#Sta/Elev= 30
       0  122.63  169.93  124.55  184.93  124.08  194.92   124.3  199.92  123.93
  214.92  121.49  219.91  121.13  229.91  120.01  288.71  104.79   293.7   104.8
  305.12  105.37  362.52  119.73  366.22  120.23  376.17     121  386.11  122.37
  410.97  122.89  415.95  123.17  470.65  123.66  500.48  122.85  510.43  123.49
  527.17  123.61  560.15  124.08  585.01  123.81  629.77   124.2  654.63  123.99
  679.49  124.28  709.33  123.93  734.19   124.1  759.06  123.85  793.86  124.01
#Mann= 4 ,-1 , 0
       0     .07       0  219.91    .015       0  376.17     .07       0
  527.17     .15       0
#XS Ineff= 2 ,-1
       0  218.81   123.8  384.89  793.86   123.8
Permanent Ineff=
       F       F
Bank Sta=219.91,376.17
XS Rating Curve= 0 ,0
Exp/Cntr=0.5,0.3

Type RM Length L Ch R = 1 ,736.1243,84.85,107.35,123.85
Node Name=B
XS GIS Cut Line= 3
3019605.97277986 13878919.1117543019606.8746809413878761.5418592
 3019727.682182113878322.3061891
#Sta/Elev= 30
       0  121.46   93.56  121.08  157.57  122.32  187.28  121.69  226.89  121.87
  231.85  121.52   236.8   120.5  260.72  113.47  267.76  112.05  276.57  110.84
  288.31  105.04  293.37  104.74  300.22  105.89  312.49  112.21  324.98  113.42
  334.85  116.22  355.64  120.98  360.59  121.73  365.54  122.04  380.39  122.09
   390.3  122.94  420.01  123.32  474.47  123.06  509.14  122.44  538.85   121.1
   553.7  121.21   563.6  121.98  578.46  122.24  598.26  121.61  613.12   121.6
#Mann= 3 , 0 , 0
       0     .07       0  226.89     .04       0  365.54     .15       0
#XS Ineff= 2 ,-1
       0   191.8   123.8  424.35  613.12   123.8
Permanent Ineff=
       F       F
Bank Sta=226.89,365.54
XS Rating Curve= 0 ,0
Exp/Cntr=0.3,0.1

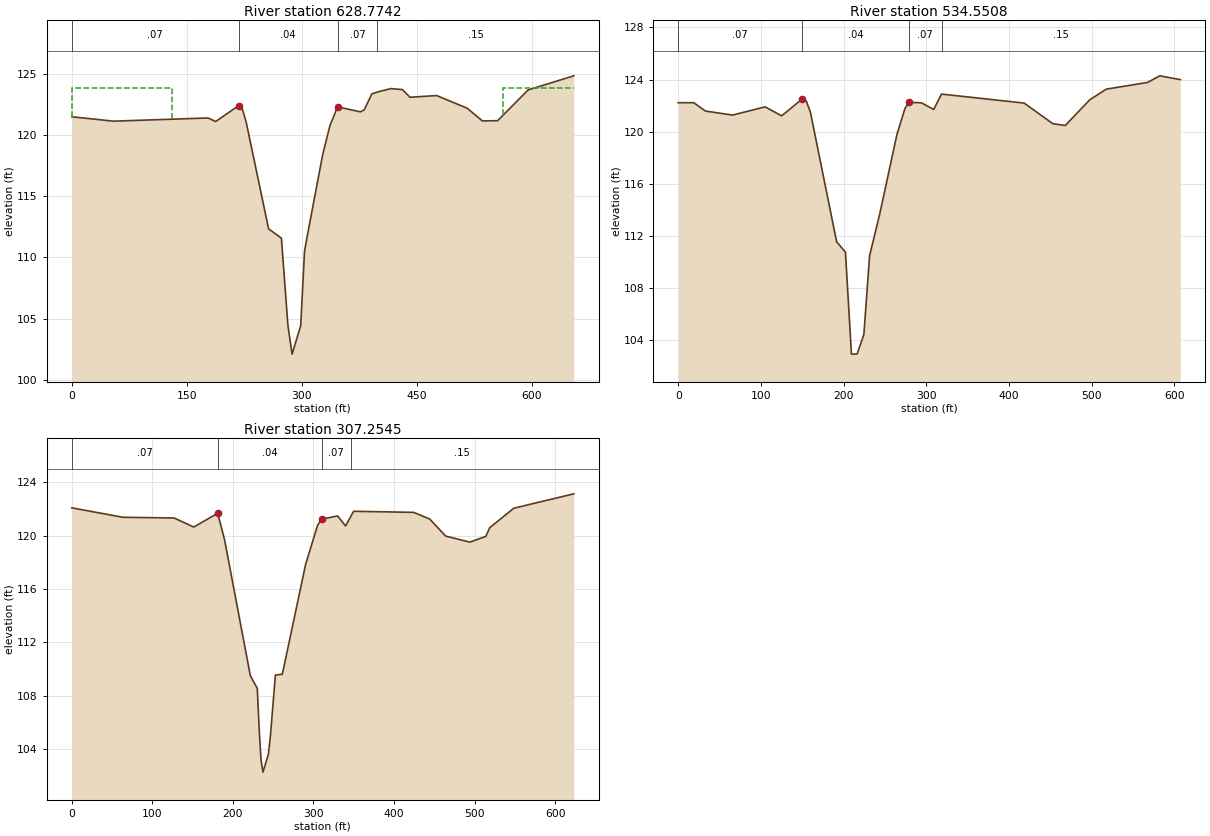
Type RM Length L Ch R = 1 ,628.7742,87.27,94.22,99.2
XS GIS Cut Line= 3
3019635.9999507813878923.99986763019640.9999407813878806.0001036
3019953.9999709413878369.9999914
#Sta/Elev= 30
       0  121.48   54.13  121.12  177.74  121.38  187.68  121.09   217.5  122.38
  222.47  122.11  227.44  121.05  256.74  112.33  273.43  111.57  281.91  104.45
  287.33  102.11  298.59  104.43  303.56   110.5  307.54  111.88  327.38  118.43
  336.77  120.77  346.71  122.29  376.53  121.88  381.49  122.05  391.43  123.35
  398.29  123.49  416.28  123.78  431.19   123.7  441.13  123.07  475.92  123.21
  515.67  122.18  535.55  121.14  555.43  121.16  595.19  123.67  654.82  124.82
#Mann= 4 ,-1 , 0
       0     .07       0   217.5     .04       0  346.71     .07       0
  398.29     .15       0
#XS Ineff= 2 ,-1
       0  130.52   123.8  562.76  654.82   123.8
Permanent Ineff=
       F       F
Bank Sta=217.5,346.71
XS Rating Curve= 0 ,0
Exp/Cntr=0.3,0.1

Type RM Length L Ch R = 1 ,534.5508,246.04,227.3,214.21
XS GIS Cut Line= 3
 3019711.717975213878908.93723373019711.8219776213878838.5978074
3020072.9757828613878441.5677616
#Sta/Elev= 30
       0  122.23   18.76  122.23   32.83  121.59   65.65  121.28  105.13  121.91
  125.01  121.22  149.85  122.51  154.82  122.36  159.79  121.51  191.54  111.56
  202.18  110.77  209.43  102.95  216.31  102.96  224.45  104.46  231.38   110.5
  243.64   113.7  264.47   119.8  274.09  121.78  279.06  122.26  293.97  122.22
  308.88  121.71  318.32  122.89  418.21   122.2     453  120.62  467.91  120.48
  497.73  122.46   517.6  123.27   567.3  123.78  582.21  124.29  607.06     124
#Mann= 4 ,-1 , 0
       0     .07       0  149.85     .04       0  279.06     .07       0
  318.32     .15       0
Bank Sta=149.85,279.06
XS Rating Curve= 0 ,0
Exp/Cntr=0.3,0.1

Type RM Length L Ch R = 1 ,307.2545,220.14,307.25,290.01
Node Name=A
XS GIS Cut Line= 5
3019794.9999608513878980.00008373019947.9999829413878948.0001477
3019973.9999309513878899.99991563020023.0001610213878797.0001216
3020168.9998690313878536.9999854
#Sta/Elev= 30
       0  122.08    63.5  121.37     127  121.32  151.43  120.64  181.12  121.67
  189.67  119.68  221.65  109.49  230.24  108.54  232.89  105.16  234.95  103.16
  237.34  102.26  244.06  103.61  246.53  104.96  252.72  109.54  261.35   109.6
  290.28  117.85  305.12  120.78  310.08  121.23  329.93  121.47  339.87  120.72
  346.14  121.42  349.81  121.82  424.36  121.74  444.24  121.24  464.12  119.96
  493.93  119.51  513.81  119.93  518.78  120.59   548.6  122.05  623.15  123.13
#Mann= 4 ,-1 , 0
       0     .07       0  181.12     .04       0  310.08     .07       0
  346.14     .15       0
Bank Sta=181.12,310.08
XS Rating Curve= 0 ,0
Exp/Cntr=0.3,0.1

Chan Stop Cuts=-1
Use User Specified Reach Order=0
Composite Channel Slope=5